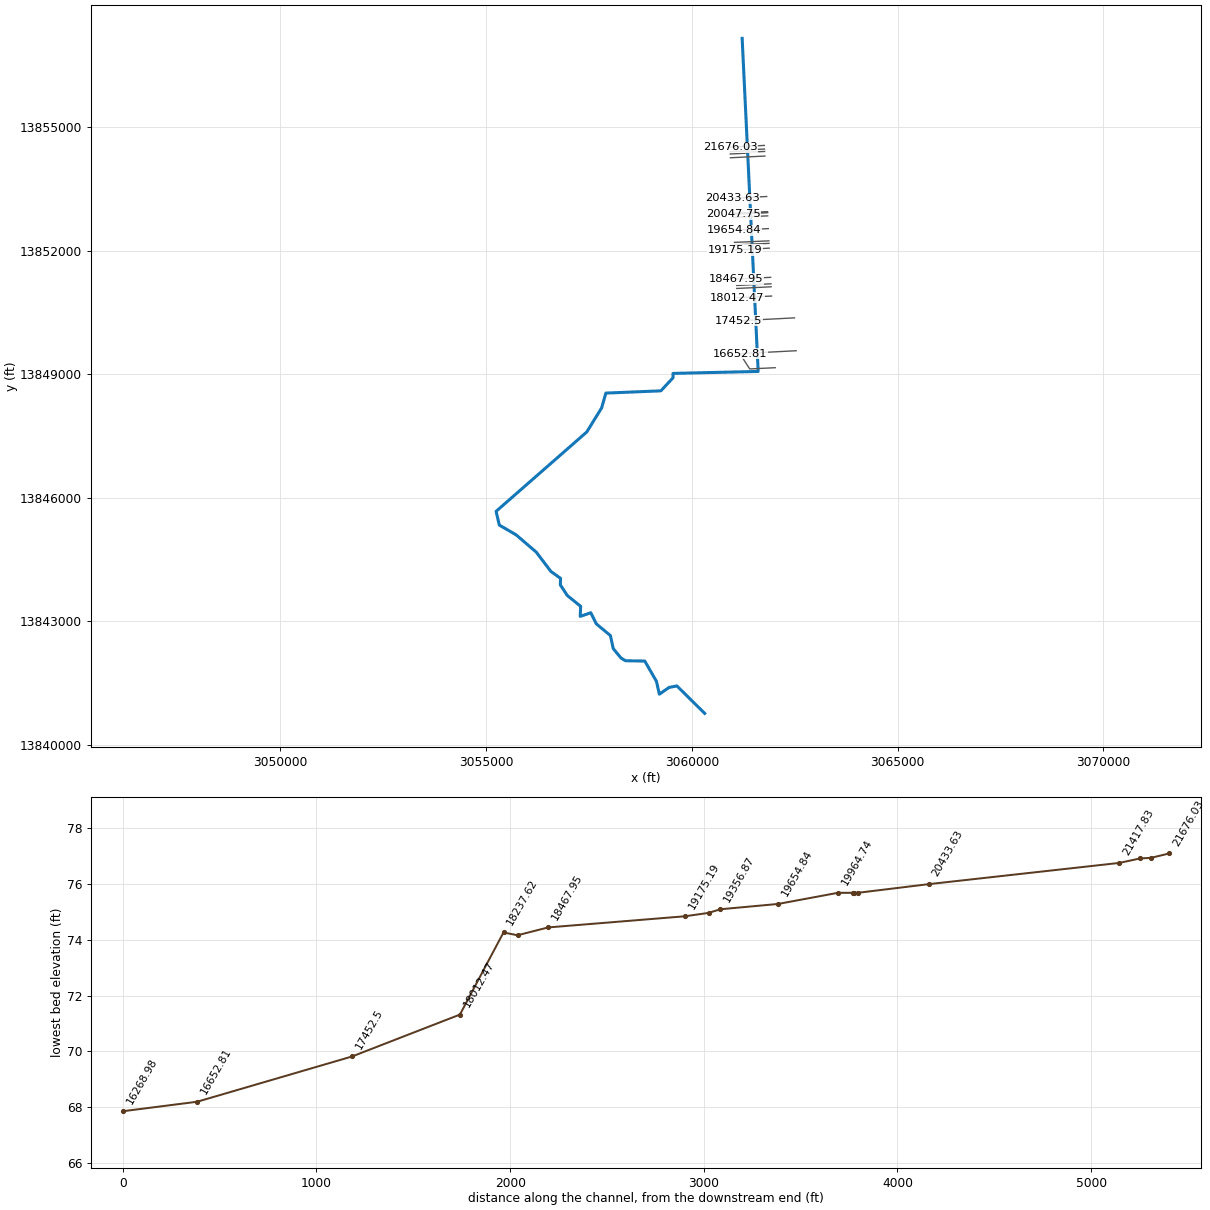
--- W156-00-00.prj (project) ---

Proj Title=W156-00-00
Current Plan=p02
Default Exp/Contr=.3,.1
English Units
Geom File=g02
Flow File=f02
Flow File=f03
Plan File=p01
Plan File=p02
Y Axis Title=Elevation
X Axis Title(PF)=Main Channel Distance
X Axis Title(XS)=Station
BEGIN DESCRIPTION:
Buffalo Bayou Watershed (Additional Stream)
Rummel Creek
HCFCD Unit W156-00-00
Flood Hazard Model
Filename: Rummel032504.prj
Prepared by:   Brown & Gay Engineers, Inc.	DATE: 03/25/2004
Reviewed by: SK/CHC/SEW			DATE: 03/25/2004
STATUS: Final
Revised
END DESCRIPTION:
DSS Export Rating Curves= 0
DSS Export Rating Curve Sorted= 0
DSS Export Volume Flow Curves= 0
DXF OffsetX= 0
DXF OffsetY= 0
DXF ScaleX= 1
DXF ScaleY= 10

--- W156-00-00.p02 (plan) ---

Plan Title=FEMA Effective MP
Version=Version 3.0.1  Mar 2001
Short Identifier=Eff+LOMR MP
Geom File=g02
Flow File=f03
Subcritical Flow
K Sum by GR= 0
Std Step Tol= 0.01
Critical Tol= 0.01
Num of Std Step Trials= 20
Max Error Tol= 0.3
Flow Tol Ratio= 0.001
Split Flow NTrial= 30
Split Flow Tol= 0.02
Split Flow Ratio= 0.02
Log Output Level= 0
Friction Slope Method= 1
Unsteady Friction Slope Method= 2
Parabolic Critical Depth
Global Vel Dist= 0 , 0 , 0
Global Log Level= 0
CheckData=True
Encroach Param=-1 ,0,0, 0
BEGIN DESCRIPTION:
FEMA Effective June 2007 + LOMR 09-06-0071P
END DESCRIPTION:
Computation Interval=1HOUR
Output Interval=1HOUR
Run HTab= 0
Run UNet= 0
Run PostProcess= 0
UNET Theta= 1
UNET ZTol= 0.02
UNET ZSATol= 0.05
UNET MxIter= 20
UNET MaxInSteps= 0
UNET DtIC= 0
UNET DtMin= 0
UNET MaxCRTS= 20
UNET WFStab= 2
UNET SFStab= 1
UNET WFX= 1
UNET SFX= 1
UNET Convert EG Bridges=-1
UNET Use Existing IB Tables=-1
Instantaneous Interval=1HOUR
Write IC File= 0
IC Time=0
Write Velocity= 0
Write Detailed= 0

--- W156-00-00.p01 (plan) ---

Plan Title=FEMA Effective FW
Version=Version 3.0.1  Mar 2001
Short Identifier=Eff+LOMR FW
Geom File=g02
Flow File=f02
Subcritical Flow
K Sum by GR= 0
Std Step Tol= 0.01
Critical Tol= 0.01
Num of Std Step Trials= 20
Max Error Tol= 0.3
Flow Tol Ratio= 0.001
Split Flow NTrial= 30
Split Flow Tol= 0.02
Split Flow Ratio= 0.02
Log Output Level= 0
Friction Slope Method= 1
Unsteady Friction Slope Method= 2
Parabolic Critical Depth
Global Vel Dist= 0 , 0 , 0
Global Log Level= 0
CheckData=True
Encroach Param=-1 ,0,0, 2
Encroach River=W156-00-00
Encroach Reach=W156-00-00_0000
Encroach Node=21676.03
       1     400  436.97
Encroach Node=21579.88
       1  400.38  438.57
Encroach Node=21551.92
       1  400.38  438.57
Encroach Node=21524.09
       1  400.83  438.48
Encroach Node=21417.83
       1     400  437.39
Encroach Node=20433.63
       1     400  437.13
Encroach Node=20067.75
       1   394.3  445.54
Encroach Node=20047.75
       1  398.02  439.08
Encroach Node=20046.25
       1  398.02  439.08
Encroach Node=20044.75
       1   396.3  437.36
Encroach Node=19964.74
       1   397.6  442.65
Encroach Node=19654.84
       1     400  437.03
Encroach Node=19356.87
       1     400  436.85
Encroach Node=19326.62
       1     400  436.85
Encroach Node=19296.35
       1  400.01  434.27
Encroach Node=19175.19
       1  400.01  434.18
Encroach Node=18467.95
       1  400.01  434.11
Encroach Node=18310.25
       1  400.13  436.05
Encroach Node=18273.94
       1  400.13  436.05
Encroach Node=18237.62
       1  400.19  436.11
Encroach Node=18012.47
       1  401.19  439.97
Encroach Node=17452.5
       1 1437.76 1476.76
Encroach Node=16652.81
       1 1399.61 1440.71
Encroach Node=16268.98
       1  400.94  439.96
Encroach Node=16233.32
       1  410.16  621.87
Encroach Node=14062.83
       4       1
Encroach Node=14061.82
       1  969.01 1180.72
Encroach Node=14026.43
       1  770.11 1099.75
Encroach Node=13982.48
       1  776.63  817.25
Encroach Node=12273.96
       4       1
Encroach Node=12273.75
       1 1151.31 1185.28
Encroach Node=12181.86
       1 1109.01 1188.53
Encroach Node=11935.25
       1 1016.18 1081.19
Encroach Node=11496.92
       1 1203.14 1289.01
Encroach Node=10717.28
       1  1241.7  1306.7
Encroach Node=9956.678
       1  903.99  997.38
Encroach Node=9850.789
       1  510.33  586.68
Encroach Node=9814.050
       1  510.33  586.68
Encroach Node=9776.550
       1  509.27  585.62
Encroach Node=9586.862
       1 1130.43 1216.94
Encroach Node=9192.376
       1  844.71  950.59
Encroach Node=8724.199
       1  974.62 1049.72
Encroach Node=8635.686
       1     973 1066.89
Encroach Node=8619.259
       1     973 1066.89
Encroach Node=8601.774
       1  967.37 1061.26
Encroach Node=8533.452
       1 1017.64 1096.81
Encroach Node=8386.468
       1  540.86  634.78
Encroach Node=8356.165
       1  546.82  628.33
Encroach Node=8354.151
       1  546.82  628.33
Encroach Node=8352.148
       1  549.83  630.03
Encroach Node=8205.582
       1  370.01  460.13
Encroach Node=7924.317
       1  393.86  576.55
Encroach Node=7827.230
       1  343.37  421.15
Encroach Node=7825.141
       1  343.37  421.15
Encroach Node=7823.121
       1  344.66  420.52
Encroach Node=7730.294
       1  343.83   511.8
Encroach Node=7440.611
       1  435.66   597.6
Encroach Node=7404.722
       1  442.51  608.79
Encroach Node=7403.695
       1  442.51  608.79
Encroach Node=7402.695
       1  444.79  608.94
Encroach Node=7335.563
       1  496.26  622.34
Encroach Node=6756.135
       1 1487.08 1695.55
Encroach Node=6503.973
       1 1325.89 1417.29
Encroach Node=6446.272
       1  304.27  484.45
Encroach Node=6403.377
       1  304.27  484.45
Encroach Node=6367.704
       1  262.59  442.76
Encroach Node=6195.197
       1  171.44  439.12
Encroach Node=6022.230
       1  267.05  437.75
Encroach Node=5966.850
       1  252.85  412.04
Encroach Node=5962.856
       1  252.85  412.04
Encroach Node=5958.857
       1  244.81     404
Encroach Node=5938.748
       1   238.5  416.63
Encroach Node=5853.792
       1   336.5  518.41
Encroach Node=5371.263
       1   429.1  674.24
Encroach Node=5285.146
       1  345.72  664.55
Encroach Node=5221.017
       1  191.27  326.08
Encroach Node=4985.114
       1     210  447.13
Encroach Node=4569.578
       1   229.3  489.13
Encroach Node=4381.730
       1  344.26  589.03
Encroach Node=4260.886
       1  438.05  722.23
Encroach Node=4203.385
       1  449.36  725.68
Encroach Node=3991.037
       1  1324.8 1557.05
Encroach Node=3804.938
       1  504.38  882.18
Encroach Node=3678.735
       1  974.71 1201.12
Encroach Node=3470.650
       1  995.31 1275.44
Encroach Node=2972.127
       1  857.93 1036.69
Encroach Node=2360.236
       1   583.9  982.96
Encroach Node=2022.700
       1  296.41   541.9
Encroach Node=1866.190
       1  155.12  511.38
Encroach Node=1681.007
       1   330.4  556.03
Encroach Node=1481.135
       1  441.18  777.47
Encroach Node=1246.119
       1  407.96  660.86
Encroach Node=1170.684
       1  443.63  715.22
Encroach Node=1163.716
       1  443.63  715.22
Encroach Node=1156.660
       1  507.34  697.91
Encroach Node=1094.514
       1  251.64  502.44
Encroach Node=1003.317
       1  224.74  539.81
Encroach Node=696.508
       1  275.03  535.03
Encroach Node=550.044
       1  261.84  326.87
Encroach Node=48.714
       1  245.92     370
BEGIN DESCRIPTION:
FEMA Effective June 2007 + LOMR 09-06-0071P
END DESCRIPTION:
Computation Interval=1HOUR
Output Interval=1HOUR
Run HTab= 0
Run UNet= 0
Run PostProcess= 0
UNET Theta= 1
UNET ZTol= 0.02
UNET ZSATol= 0.05
UNET MxIter= 20
UNET MaxInSteps= 0
UNET DtIC= 0
UNET DtMin= 0
UNET MaxCRTS= 20
UNET WFStab= 2
UNET SFStab= 1
UNET WFX= 1
UNET SFX= 1
UNET Convert EG Bridges=-1
UNET Use Existing IB Tables=-1
Instantaneous Interval=1HOUR
Write IC File= 0
IC Time=0
Write Velocity= 0
Write Detailed= 0

--- W156-00-00.f03 (steady flow) ---

Flow Title=FEMA Effective June 2007
Program Version=3.13
Number of Profiles= 4
Profile Names=10PCT_10yr,2PCT_50yr,1PCT_100yr,0.2PCT_500yr
River Rch & RM=W156-00-00,W156-00-00_0000 ,21676.03
     240     343     397     555
River Rch & RM=W156-00-00,W156-00-00_0000 ,21417.83
     250     359     416     582
River Rch & RM=W156-00-00,W156-00-00_0000 ,20433.63
     289     418     487     684
River Rch & RM=W156-00-00,W156-00-00_0000 ,20067.75
     303     441     513     722
River Rch & RM=W156-00-00,W156-00-00_0000 ,19654.84
     319     466     543     764
River Rch & RM=W156-00-00,W156-00-00_0000 ,19175.19
     338     495     578     814
River Rch & RM=W156-00-00,W156-00-00_0000 ,18467.95
     365     538     629     887
River Rch & RM=W156-00-00,W156-00-00_0000 ,18012.47
     383     566     661     934
River Rch & RM=W156-00-00,W156-00-00_0000 ,17452.5
     405     600     702     992
River Rch & RM=W156-00-00,W156-00-00_0000 ,16652.81
     436     648     760    1075
River Rch & RM=W156-00-00,W156-00-00_0000 ,16268.98
     451     671     787    1115
River Rch & RM=W156-00-00,W156-00-00_0000 ,16233.32
     453     674     790    1119
River Rch & RM=W156-00-00,W156-00-00_0000 ,14061.82
     771     900     900     900
River Rch & RM=W156-00-00,W156-00-00_0000 ,12273.75
     815     900     900     900
River Rch & RM=W156-00-00,W156-00-00_0000 ,12181.86
    1531    2295    2699    3812
River Rch & RM=W156-00-00,W156-00-00_0000 ,11496.92
    1576    2376    2798    3949
River Rch & RM=W156-00-00,W156-00-00_0000 ,10717.28
    1601    2421    2853    4025
River Rch & RM=W156-00-00,W156-00-00_0000 ,9586.862
    1663    2532    2989    4214
River Rch & RM=W156-00-00,W156-00-00_0000 ,8724.199
    1696    2591    3061    4313
River Rch & RM=W156-00-00,W156-00-00_0000 ,8205.582
    1725    2642    3123    4399
River Rch & RM=W156-00-00,W156-00-00_0000 ,7440.611
    1756    2698    3191    4494
River Rch & RM=W156-00-00,W156-00-00_0000 ,6756.135
    1789    2756    3263    4593
River Rch & RM=W156-00-00,W156-00-00_0000 ,6022.230
    1822    2816    3336    4694
River Rch & RM=W156-00-00,W156-00-00_0000 ,5371.263
    1856    2876    3409    4796
River Rch & RM=W156-00-00,W156-00-00_0000 ,4985.114
    1882    2923    3466    4875
River Rch & RM=W156-00-00,W156-00-00_0000 ,4381.730
    1915    2983    3540    4976
River Rch & RM=W156-00-00,W156-00-00_0000 ,3991.037
    1942    3032    3599    5059
River Rch & RM=W156-00-00,W156-00-00_0000 ,3470.650
    1974    3088    3667    5154
River Rch & RM=W156-00-00,W156-00-00_0000 ,2972.127
    2000    3135    3726    5234
River Rch & RM=W156-00-00,W156-00-00_0000 ,2360.236
    2032    3193    3796    5332
River Rch & RM=W156-00-00,W156-00-00_0000 ,1866.190
    2061    3244    3859    5419
River Rch & RM=W156-00-00,W156-00-00_0000 ,1481.135
    2083    3283    3907    5485
River Rch & RM=W156-00-00,W156-00-00_0000 ,1003.317
    2113    3338    3973    5577
River Rch & RM=W156-00-00,W156-00-00_0000 ,550.044
    2139    3383    4028    5654
River Rch & RM=W156-00-00,W156-00-00_0000 ,48.714
    2163    3427    4082    5728
Boundary for River Rch & Prof#=W156-00-00,W156-00-00_0000 , 1
Up Type= 0
Dn Type= 3
Dn Slope=0.002
Boundary for River Rch & Prof#=W156-00-00,W156-00-00_0000 , 2
Up Type= 0
Dn Type= 3
Dn Slope=0.002
Boundary for River Rch & Prof#=W156-00-00,W156-00-00_0000 , 3
Up Type= 0
Dn Type= 3
Dn Slope=0.002
Boundary for River Rch & Prof#=W156-00-00,W156-00-00_0000 , 4
Up Type= 0
Dn Type= 3
Dn Slope=0.002
DSS Import GetInterval= 0
DSS Import GetPeak= 0
DSS Import FillOption= 0

--- W156-00-00.f02 (steady flow) ---

Flow Title=Floodway
Program Version=3.13
Number of Profiles= 2
Profile Names=1PCT_100_YR,1PCT_Floodway_100yrFW
River Rch & RM=W156-00-00,W156-00-00_0000 ,21676.03
     397     397
River Rch & RM=W156-00-00,W156-00-00_0000 ,21417.83
     416     416
River Rch & RM=W156-00-00,W156-00-00_0000 ,20433.63
     487     487
River Rch & RM=W156-00-00,W156-00-00_0000 ,20067.75
     513     513
River Rch & RM=W156-00-00,W156-00-00_0000 ,19654.84
     543     543
River Rch & RM=W156-00-00,W156-00-00_0000 ,19175.19
     578     578
River Rch & RM=W156-00-00,W156-00-00_0000 ,18467.95
     629     629
River Rch & RM=W156-00-00,W156-00-00_0000 ,18012.47
     661     661
River Rch & RM=W156-00-00,W156-00-00_0000 ,17452.5
     702     702
River Rch & RM=W156-00-00,W156-00-00_0000 ,16652.81
     760     760
River Rch & RM=W156-00-00,W156-00-00_0000 ,16268.98
     787     787
River Rch & RM=W156-00-00,W156-00-00_0000 ,16233.32
     790     790
River Rch & RM=W156-00-00,W156-00-00_0000 ,14061.82
     900     900
River Rch & RM=W156-00-00,W156-00-00_0000 ,12273.75
     900     900
River Rch & RM=W156-00-00,W156-00-00_0000 ,12181.86
    2699    2699
River Rch & RM=W156-00-00,W156-00-00_0000 ,11496.92
    2798    2798
River Rch & RM=W156-00-00,W156-00-00_0000 ,10717.28
    2853    2853
River Rch & RM=W156-00-00,W156-00-00_0000 ,9586.862
    2989    2989
River Rch & RM=W156-00-00,W156-00-00_0000 ,8724.199
    3061    3061
River Rch & RM=W156-00-00,W156-00-00_0000 ,8205.582
    3123    3123
River Rch & RM=W156-00-00,W156-00-00_0000 ,7440.611
    3191    3191
River Rch & RM=W156-00-00,W156-00-00_0000 ,6756.135
    3263    3263
River Rch & RM=W156-00-00,W156-00-00_0000 ,6022.230
    3336    3336
River Rch & RM=W156-00-00,W156-00-00_0000 ,5371.263
    3409    3409
River Rch & RM=W156-00-00,W156-00-00_0000 ,4985.114
    3466    3466
River Rch & RM=W156-00-00,W156-00-00_0000 ,4381.730
    3540    3540
River Rch & RM=W156-00-00,W156-00-00_0000 ,3991.037
    3599    3599
River Rch & RM=W156-00-00,W156-00-00_0000 ,3470.650
    3667    3667
River Rch & RM=W156-00-00,W156-00-00_0000 ,2972.127
    3726    3726
River Rch & RM=W156-00-00,W156-00-00_0000 ,2360.236
    3796    3796
River Rch & RM=W156-00-00,W156-00-00_0000 ,1866.190
    3859    3859
River Rch & RM=W156-00-00,W156-00-00_0000 ,1481.135
    3907    3907
River Rch & RM=W156-00-00,W156-00-00_0000 ,1003.317
    3973    3973
River Rch & RM=W156-00-00,W156-00-00_0000 ,550.044
    4028    4028
River Rch & RM=W156-00-00,W156-00-00_0000 ,48.714
    4082    4082
Boundary for River Rch & Prof#=W156-00-00,W156-00-00_0000 , 1
Up Type= 0
Dn Type= 3
Dn Slope=0.002
Boundary for River Rch & Prof#=W156-00-00,W156-00-00_0000 , 2
Up Type= 0
Dn Type= 3
Dn Slope=0.002
DSS Import GetInterval= 0
DSS Import GetPeak= 0
DSS Import FillOption= 0

--- W156-00-00.g02 (geometry) ---

Geom Title=W156-00-00
Version=Version 3.0.1  Mar 2001

River Reach=W156-00-00      ,W156-00-00_0000
Reach XY= 30
     3061220.338    13857166.211     3061610.144    13849071.415
     3059540.327    13849024.199     3059541.425    13848918.787
     3059244.953    13848600.353     3057908.631    13848545.451
     3057806.512     13848186.39     3057443.608    13847599.533
     3055241.119    13845672.031     3055319.438    13845338.607
     3055731.205     13845098.41     3056217.791    13844679.872
     3056573.955    13844210.365     3056808.018    13844043.859
       3056801.8    13843885.069     3056972.758    13843625.195
     3057295.728    13843365.047     3057285.361    13843119.323
     3057541.858    13843208.001     3057677.492    13842936.631
     3058019.524    13842653.662     3058086.973    13842338.465
     3058274.133    13842109.942     3058384.011    13842041.427
     3058854.861    13842033.644     3059136.333    13841543.338
     3059208.971    13841229.438     3059446.719    13841393.876
     3059634.759    13841429.563     3060310.057      13840762.5

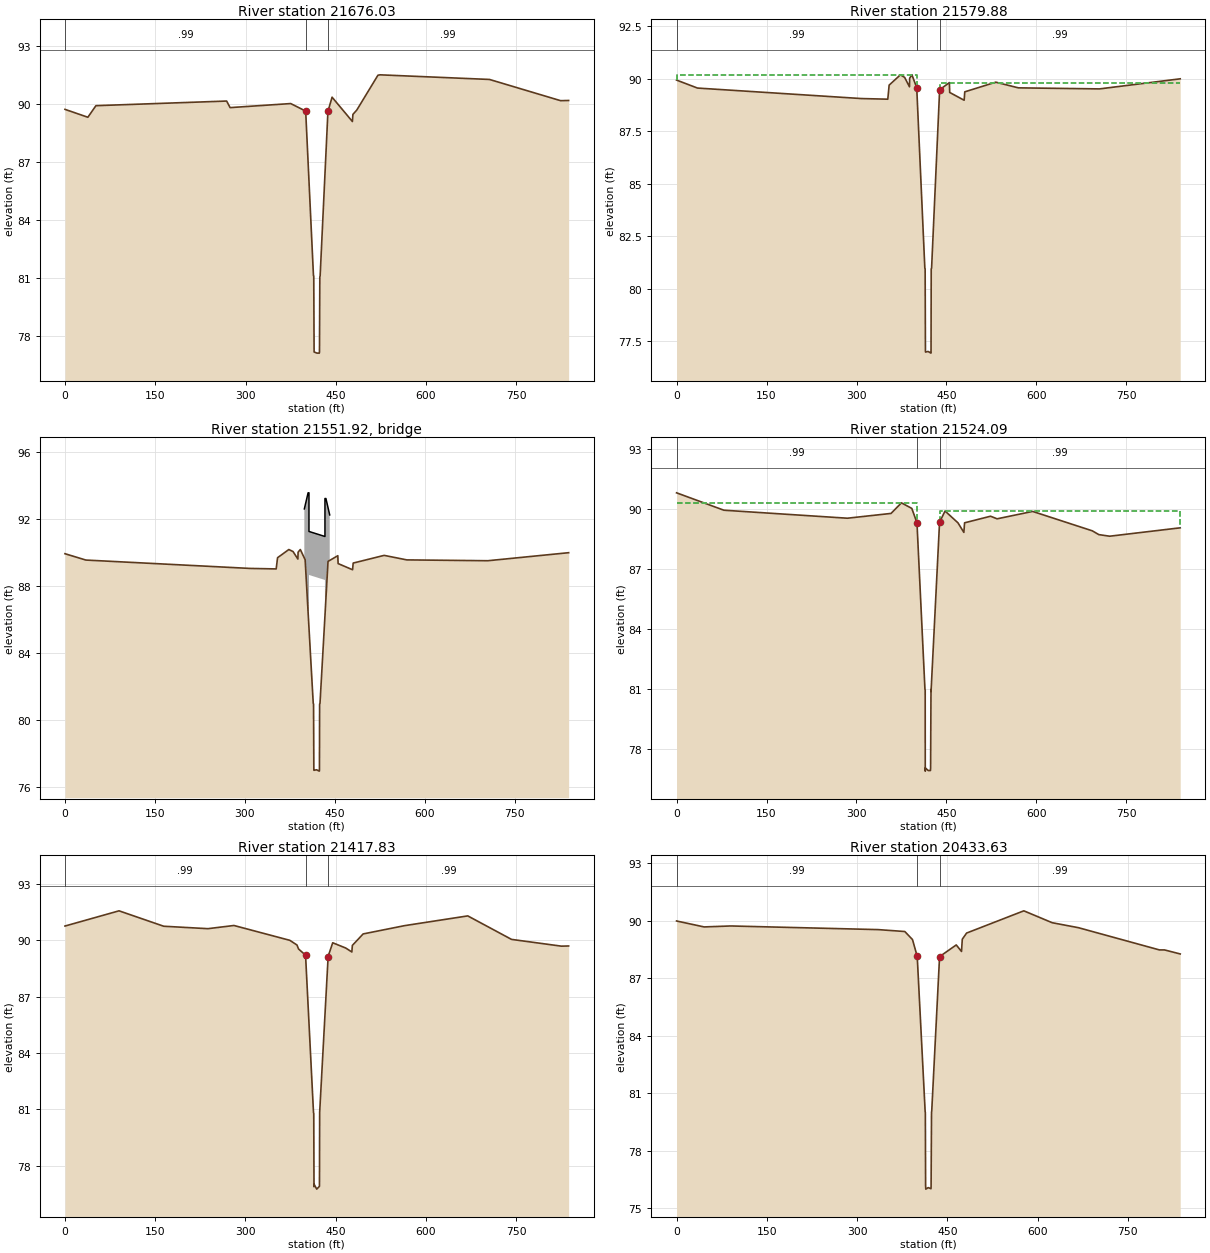
Type RM Length L Ch R = 1 ,21676.03,87.96,95.76,110.1
BEGIN DESCRIPTION:
P
END DESCRIPTION:
XS GIS Cut Line= 2
     3061759.652    13854563.687     3060923.728    13854521.691
#Sta/Elev= 25
       0   89.73   38.05   89.32   51.43   89.92  268.65   90.16  274.43   89.82
  375.11   90.03     400   89.64  412.94    81.1  413.42   81.09  413.99   77.15
  418.81   77.09  422.66   77.09  422.93   77.16  423.51   81.03  424.06   81.11
  436.97   89.62  443.88   90.36  477.63    89.1   478.5   89.47  484.87   89.69
   520.1    91.5  523.65   91.52  705.47   91.28   823.6   90.18  836.98   90.19
#Mann= 3 ,-1 , 0
       0     .99       0     400    .015       0  436.97     .99       0
Bank Sta=400,436.97
XS Rating Curve= 0
Exp/Cntr=.5,.3

Type RM Length L Ch R = 1 ,21579.88,56.77,55.69,55.98
BEGIN DESCRIPTION:
u/s of Chatterton St. Bridge
END DESCRIPTION:
XS GIS Cut Line= 4
     3061764.027    13854475.924     3061384.329    13854456.716
     3061280.634    13854429.463     3060928.815    13854411.666
#Sta/Elev= 29
       0   89.93   34.81   89.55  308.22   89.05  352.14   89.02   354.4   89.69
   373.2   90.18  380.18   90.06   388.3   89.61  388.63   90.02  392.36   90.18
  400.38   89.57  413.89   80.98  414.41   80.94  414.89   77.05  415.03   76.98
 419.359   77.01  424.11   76.93  424.23      77  424.53   80.94  425.16   80.98
  438.57   89.47  454.85   89.81  455.35   89.34  479.47   88.97  480.47   89.37
  532.12   89.83  569.91   89.56  704.95   89.51  839.67   89.99
#Mann= 3 ,-1 , 0
       0     .99       0  400.38    .015       0  438.57     .99       0
#XS Ineff= 2 , 0
       0  400.38   90.18  438.57       0   89.81
Permanent Ineff=
       F       F
Bank Sta=400.38,438.57
XS Rating Curve= 0
Exp/Cntr=.5,.3

Type RM Length L Ch R = 3 ,21551.92,,,
BEGIN DESCRIPTION:
Chatterton St. Bridge
END DESCRIPTION:
Bridge Culvert--1,0,-1,-1, 0
Deck Dist Width WeirC Skew NumUp NumDn MinLoCord MaxHiCord MaxSubmerge Is_Ogee
.3,55,2.6,0, 8, 8, 90.96, , .95, 0, 0,0,,
  399.06  405.31  406.78  406.78  433.41  433.41  435.04  441.33
   92.61   93.57   93.57   91.26   90.96   93.23   93.23   92.25
   86.53   86.53   86.53   88.66   88.36   85.99   85.99   85.99
     399  405.34  407.24  407.24  433.69  433.69  435.07   441.2
   92.36   93.29   93.29   90.98   91.23   93.54   93.54   92.53
   85.95   85.95   85.95   88.38   88.63   86.23   86.23   86.23
BR Coef=-1 , 0 , 0 ,, 0 ,,,.8,-1,,0,
WSPro=,,,, 1 ,,,, 0 ,,,, 0 ,,,,-1 ,-1 ,-1 , 0 , 0 , 0 , 0 , 0
BC Design=,, 0 ,, 0 ,,,,,,
BC HTab HWMax=90.18

Type RM Length L Ch R = 1 ,21524.09,113.47,106.75,92.15
BEGIN DESCRIPTION:
d/s of Chatterton St. Bridge
END DESCRIPTION:
XS GIS Cut Line= 4
     3061766.839    13854417.046     3061387.017    13854401.347
      3061284.74    13854373.796     3060931.514    13854355.592
#Sta/Elev= 28
       0   90.83   78.95   89.96  284.81   89.56   357.6    89.8  374.95   90.33
   392.2   90.05  400.83   89.33  414.14      81  414.54   80.97  414.65   76.91
  414.73   77.07  419.58   76.94  423.27   76.94  423.56   77.06  424.22   80.99
  424.33    80.9  438.48   89.36  447.65   89.92  469.17   89.33  479.02   88.85
   480.2   89.33  523.51   89.66  534.42   89.53   593.7    89.9  693.09   88.93
  704.04   88.74  722.05   88.66  839.76   89.08
#Mann= 3 ,-1 , 0
       0     .99       0  400.83    .015       0  438.48     .99       0
#XS Ineff= 2 , 0
       0  400.83   90.33  438.48       0   89.92
Permanent Ineff=
       F       F
Bank Sta=400.83,438.48
XS Rating Curve= 0
Exp/Cntr=.5,.3

Type RM Length L Ch R = 1 ,21417.83,984.2,984.18,984.33
XS GIS Cut Line= 2
      3061772.37    13854305.806     3060936.036     13854263.79
#Sta/Elev= 28
       0   90.75   89.87   91.56  164.14   90.74  237.66   90.61  280.92   90.78
  373.83   89.99  385.76   89.74  388.32   89.53     400    89.2  413.19   80.83
  413.62   80.78  414.03   76.88  414.34      77  418.55   76.75  423.12    76.9
  423.44   80.83  437.12   88.88  437.39   89.12  445.12   89.86   466.8   89.58
  476.95   89.37  477.82   89.72  495.69   90.33  564.41   90.77  669.68   91.29
  742.41   90.04  825.29   89.68  837.39   89.69
#Mann= 3 ,-1 , 0
       0     .99       0     400    .015       0  437.39     .99       0
Bank Sta=400,437.39
XS Rating Curve= 0
Exp/Cntr=.3,.1

Type RM Length L Ch R = 1 ,20433.63,366.93,365.88,364.63
XS GIS Cut Line= 2
     3061819.011    13853322.728     3060982.946    13853280.725
#Sta/Elev= 27
       0   89.98   45.76   89.67   90.05   89.72  334.85   89.53  379.37   89.43
  392.13   89.01     400   88.13  413.18   80.03  413.48   79.99  413.93   76.16
  414.26   75.99  418.32   76.07  422.88   76.01  423.03   76.12  423.74   79.99
  424.12   80.07  437.13   88.12  464.85   88.73  473.59   88.39  474.89   89.03
  482.09   89.35  577.15   90.51  624.29   89.89  667.95   89.63  802.58   88.47
  811.03   88.47  837.12   88.26
#Mann= 3 ,-1 , 0
       0     .99       0     400    .015       0  437.13     .99       0
Bank Sta=400,437.13
XS Rating Curve= 0
Exp/Cntr=.3,.1

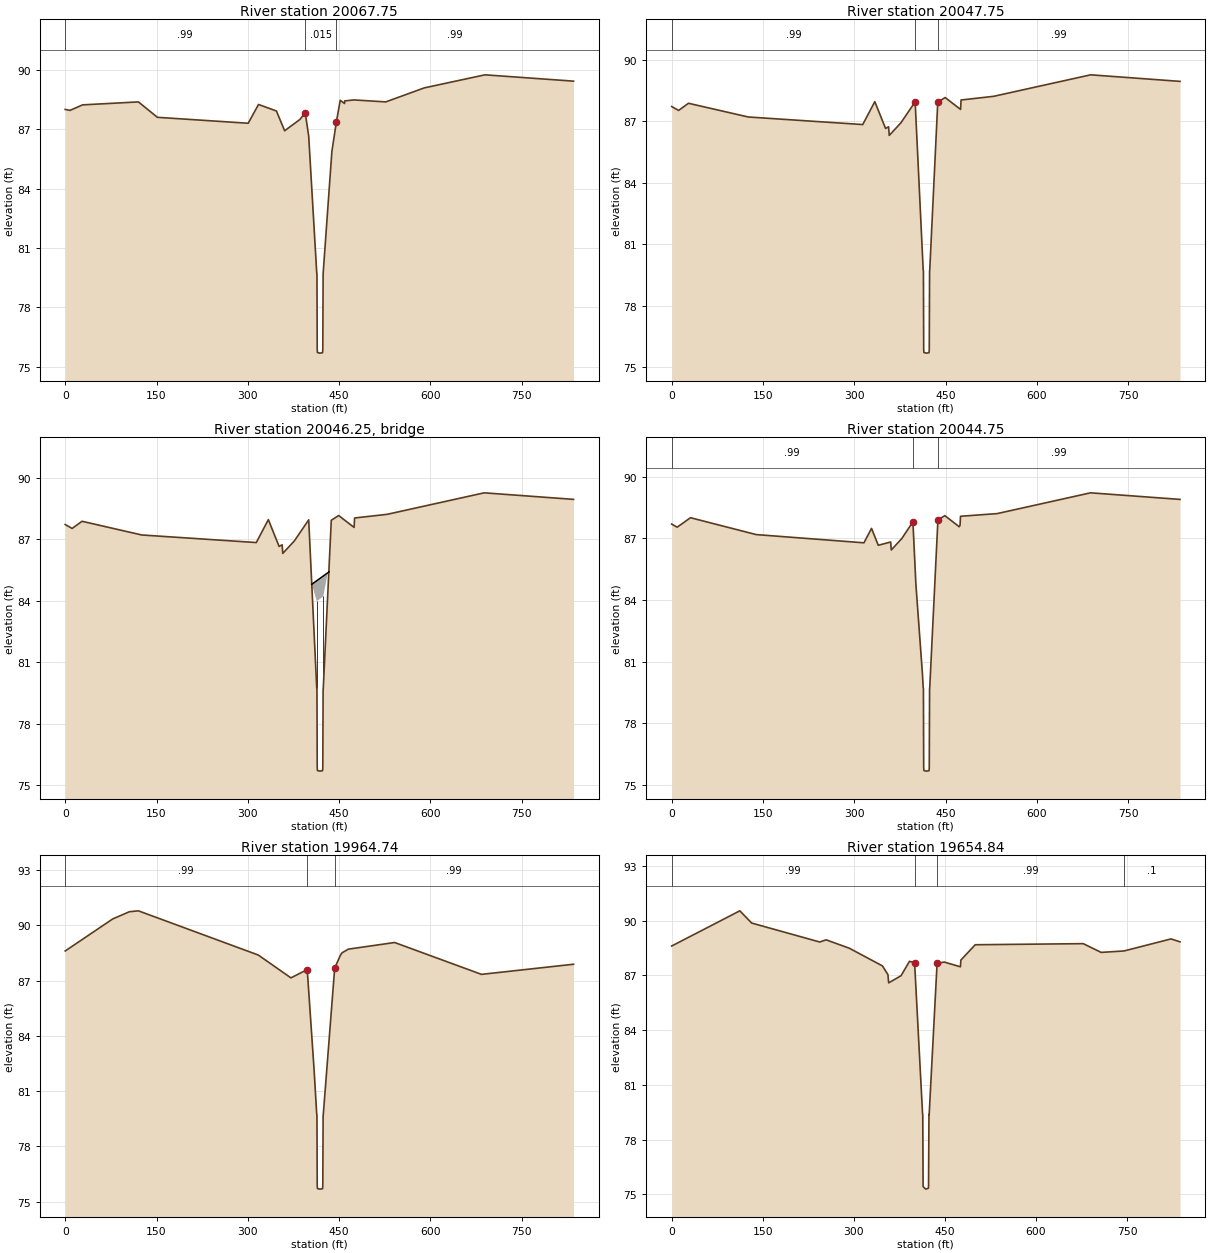
Type RM Length L Ch R = 1 ,20067.75,20,20,20.01
BEGIN DESCRIPTION:
O
END DESCRIPTION:
XS GIS Cut Line= 2
     3061836.663    13852954.788     3061002.438    13852917.861
#Sta/Elev= 30
       0   88.01    7.82   87.96   28.58   88.24  120.31   88.39  151.44   87.61
  300.63   87.31  317.58   88.26  346.96   87.93  360.49   86.93  385.49    87.5
   394.3   87.84  399.99   86.66  413.17   79.75  413.55    79.7  413.99   75.87
  414.34   75.71  418.34   75.68  422.72    75.7  423.15   75.83  423.67   79.69
  438.09   85.89  445.54   87.39  451.76   88.47  458.91   88.31  459.15   88.44
   474.3   88.49  526.61   88.39  589.93    89.1  689.63   89.76  835.04   89.44
#Mann= 3 ,-1 , 0
       0     .99       0   394.3    .015       0  445.54     .99       0
Bank Sta=394.3,445.54
XS Rating Curve= 0
Exp/Cntr=.5,.3

Type RM Length L Ch R = 1 ,20047.75,3,3,3
BEGIN DESCRIPTION:
u/s of 12" pipeline
END DESCRIPTION:
XS GIS Cut Line= 2
     3061837.548    13852934.808     3061003.323     13852897.88
#Sta/Elev= 27
       0   87.73   11.41   87.54   27.62   87.89  125.75   87.22  313.87   86.85
   333.7   87.97  351.39   86.66  356.37   86.74  357.43   86.32  376.44   86.93
  399.99   87.96  413.17   79.75  413.55    79.7  413.99   75.87  414.34   75.71
  418.34   75.68  422.72    75.7  423.15   75.83  423.67   79.69  423.88    79.7
  437.11   87.94  449.24   88.17  474.56   87.59  475.41   88.05  529.02   88.23
   688.3   89.28  835.04   88.96
#Mann= 3 ,-1 , 0
       0     .99       0  399.99    .015       0  437.11     .99       0
Bank Sta=399.99,437.11
XS Rating Curve= 0
Exp/Cntr=.5,.3

Type RM Length L Ch R = 3 ,20046.25,,,
BEGIN DESCRIPTION:
12" pipe
END DESCRIPTION:
Bridge Culvert--1,0,-1,-1, 0
Deck Dist Width WeirC Skew NumUp NumDn MinLoCord MaxHiCord MaxSubmerge Is_Ogee
1,1,3,0, 2, 2, 84.81, , .95, 0, 0,0,,
     405   433.5
   84.81   85.42
   83.81   84.42
     401  433.35
   84.81   85.42
   83.81   84.42
Pier Skew, UpSta & Num, DnSta & Num=  ,413.3, 2 ,413.3, 2 , 0 , 0 , 0 ,,
      .5      .5
   83.95   84.42
      .5      .5
      84   84.42
Pier Skew, UpSta & Num, DnSta & Num=  ,423.92, 2 ,423.92, 2 , 0 , 0 , 0 ,,
      .5      .5
      84   84.42
      .5      .5
      84   84.42
BR Coef=-1 , 1 , 1 ,1.25, 0 ,,,.8,0,2,0,
WSPro=,,,, 1 ,,,, 0 ,,,, 0 ,,,,-1 ,-1 ,-1 , 0 , 0 , 0 , 0 , 0
BC Design=,, 0 ,, 0 ,,,,,,
BC HTab HWMax=89.28

Type RM Length L Ch R = 1 ,20044.75,80,80,80.02
BEGIN DESCRIPTION:
d/s of 12" pipeline
END DESCRIPTION:
XS GIS Cut Line= 2
      3061837.68    13852931.811     3061003.456    13852894.883
#Sta/Elev= 30
       0   87.69    9.06   87.54   30.89      88  138.81   87.18  315.86   86.78
  328.31   87.48  339.42   86.66  359.75   86.82  360.71   86.43  378.08   86.99
   396.3    87.8  401.15   84.78  411.98   80.39  413.17   79.75  413.55    79.7
  413.99   75.87  414.34   75.71  418.34   75.68  422.72    75.7  423.15   75.83
  423.67   79.69  423.88    79.7  437.36   87.89  448.73    88.1  472.45   87.56
  473.69   87.63   474.5   88.07  534.65    88.2   688.1   89.21  835.04   88.89
#Mann= 3 ,-1 , 0
       0     .99       0   396.3    .015       0  437.36     .99       0
Bank Sta=396.3,437.36
XS Rating Curve= 0
Exp/Cntr=.5,.3

Type RM Length L Ch R = 1 ,19964.74,309.9,309.91,309.98
XS GIS Cut Line= 2
     3061841.218    13852851.889     3061006.993    13852814.961
#Sta/Elev= 24
       0   88.61   78.09   90.35  105.37   90.74  120.21   90.79  317.18   88.39
  370.79   87.15   397.6    87.6  408.89   82.14  413.17   79.75  413.55    79.7
  413.99   75.87  414.34   75.71  418.34   75.68  422.72    75.7  423.15   75.83
  423.67   79.69  423.88    79.7  442.65   87.67  451.93   88.37  454.73   88.51
  465.25   88.71  541.14   89.07  683.79   87.34  835.04   87.89
#Mann= 3 ,-1 , 0
       0     .99       0   397.6    .015       0  442.65     .99       0
Bank Sta=397.6,442.65
XS Rating Curve= 0
Exp/Cntr=.3,.1

Type RM Length L Ch R = 1 ,19654.84,297.97,297.97,298.05
BEGIN DESCRIPTION:
N
END DESCRIPTION:
XS GIS Cut Line= 2
     3061856.171    13852542.344     3061019.963    13852505.329
#Sta/Elev= 30
       0   88.61  112.27   90.54  131.73   89.87  243.83   88.83  254.38   88.95
  292.45   88.49   347.1   87.52  356.15   87.04   357.3   86.59   377.6   86.98
  391.59   87.77     400    87.7  413.15    79.4  413.46   79.37     414   75.42
  418.32   75.28  422.68   75.33  422.97   75.43  423.65   79.37     424   79.36
  437.03   87.66  448.94   87.73  475.47   87.47   476.2   87.84  499.85   88.68
  677.68   88.74   707.2   88.26  744.95   88.34  822.31      89  837.03   88.84
#Mann= 4 ,-1 , 0
       0     .99       0     400    .015       0  437.03     .99       0
  744.95      .1       0
Bank Sta=400,437.03
XS Rating Curve= 0
Exp/Cntr=.5,.3

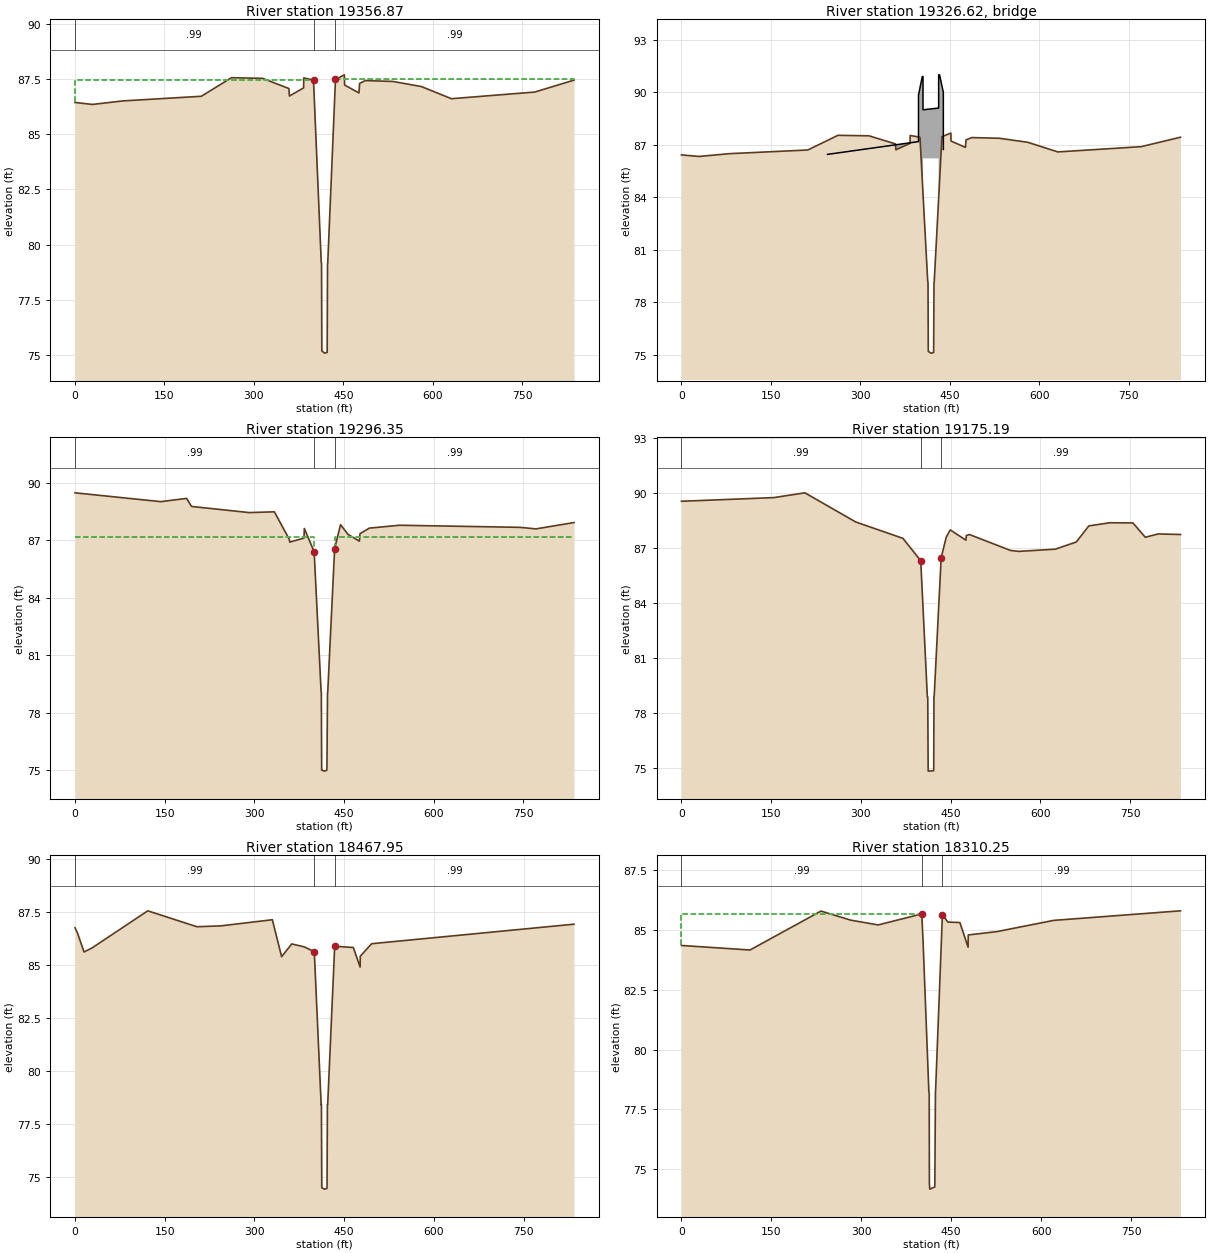
Type RM Length L Ch R = 1 ,19356.87,60.52,60.52,60.53
BEGIN DESCRIPTION:
u/s of Shadow Oaks Drive bridge
END DESCRIPTION:
XS GIS Cut Line= 2
     3061870.291    13852244.707     3061034.254      13852207.7
#Sta/Elev= 30
       0   86.43   29.31   86.34   80.36    86.5   211.9   86.71  262.51   87.55
  314.59   87.52  358.82   87.06  359.57   86.72  383.41   87.09  383.62   87.54
     400   87.44  413.02   79.18  413.48   79.16  413.96   75.19  418.48   75.09
   422.8   75.12  422.92    75.2  423.52   79.12  423.84   79.14  436.85   87.47
  451.76   87.68  452.14   87.22  476.24   86.86  477.33   87.29  486.75   87.42
  533.31   87.38  580.86   87.15  631.24    86.6  770.94    86.9  836.86   87.44
#Mann= 3 ,-1 , 0
       0     .99       0     400    .015       0  436.85     .99       0
#XS Ineff= 2 , 0
       0     400   87.44  436.85       0   87.47
Permanent Ineff=
       F       F
Bank Sta=400,436.85
XS Rating Curve= 0
Exp/Cntr=.5,.3

Type RM Length L Ch R = 3 ,19326.62,,,
BEGIN DESCRIPTION:
Shadow Oaks Drive Bridge
END DESCRIPTION:
Bridge Culvert--1,0,-1,-1, 0
Deck Dist Width WeirC Skew NumUp NumDn MinLoCord MaxHiCord MaxSubmerge Is_Ogee
3.325,53.87,2.6,0, 11, 11, 86.46, , .95, 0, 0,0,,
     245  397.53  397.53  403.88  405.09  405.09  431.32  431.32  432.86  439.19
  439.19
   86.46   87.19   89.85   90.91   90.91   89.01   89.11   91.01   91.01   90.01
   86.74
                   84.01   84.01   84.01   86.23   86.23    83.9    83.9    83.9
        
     245  396.79  396.79  403.04  404.42  404.42  430.54  430.54  432.02  438.33
  438.33
   86.46   87.19   89.81      91      91   88.72   88.92   90.92   90.92   89.92
   86.74
                   84.06   84.06   84.06   86.05   86.25   84.14   84.14   84.14
        
BR Coef=-1 , 0 , 0 ,, 0 ,,,.8,-1,,0,
WSPro=,,,, 1 ,,,, 0 ,,,, 0 ,,,,-1 ,-1 ,-1 , 0 , 0 , 0 , 0 , 0
BC Design=,, 0 ,, 0 ,,,,,,
BC HTab HWMax=87.68

Type RM Length L Ch R = 1 ,19296.35,119.39,121.12,123.21
BEGIN DESCRIPTION:
d/s of Shadow Oaks Drive bridge
END DESCRIPTION:
XS GIS Cut Line= 2
     3061872.603    13852184.231     3061038.823    13852147.324
#Sta/Elev= 30
       0   89.47  143.48   89.01  186.83   89.18  194.78   88.76  291.46   88.44
  333.46   88.48  358.38   87.05  359.19    86.9     383   87.11  383.57   87.61
  400.01    86.4  411.66   79.09  412.01   79.07  412.57   75.06  412.59   75.01
  417.14   74.96  420.99      75  421.35   75.09  422.34   79.03  422.69   79.06
  434.27   86.56  444.17   87.81  456.73    87.3  475.73   86.95  476.62   87.34
  492.35   87.63  543.02   87.78  744.25   87.67  770.91   87.59   834.6   87.92
#Mann= 3 ,-1 , 0
       0     .99       0  400.01    .015       0  434.27     .99       0
#XS Ineff= 2 , 0
       0  400.01   87.19  434.27       0   87.19
Permanent Ineff=
       F       F
Bank Sta=400.01,434.27
XS Rating Curve= 0
Exp/Cntr=.5,.3

Type RM Length L Ch R = 1 ,19175.19,708.23,707.25,706.2
XS GIS Cut Line= 2
     3061877.983    13852067.431     3061045.016    13852022.093
#Sta/Elev= 30
       0   89.54  154.59   89.74  206.37      90  291.46   88.41  370.29   87.52
  400.01    86.3  411.07   78.88  411.75   78.87   412.4   74.97  412.61   74.84
  421.62   74.86  421.72   75.03  422.11   78.89  422.55   78.95  434.18   86.47
  442.73   87.59  449.35   87.98  475.63   87.42  476.15   87.67  481.29   87.73
  550.25   86.86  563.96   86.81  624.88   86.93  659.95   87.32  681.09    88.2
  716.47   88.37  754.69   88.36  775.43   87.58  796.85   87.76   834.2   87.73
#Mann= 3 ,-1 , 0
       0     .99       0  400.01    .015       0  434.18     .99       0
Bank Sta=400.01,434.18
XS Rating Curve= 0
Exp/Cntr=.3,.1

Type RM Length L Ch R = 1 ,18467.95,157.7,157.7,157.73
BEGIN DESCRIPTION:
M - Floodplain mapping based on WSEL
END DESCRIPTION:
XS GIS Cut Line= 2
     3061912.052    13851358.624     3061078.925    13851318.084
#Sta/Elev= 26
       0   86.76    4.23   86.51   15.14   85.62   28.47   85.81  121.67   87.56
  203.83   86.81  243.59   86.85  329.89   87.14  345.37    85.4  362.34      86
  383.28   85.86  400.01   85.63  411.49   78.42   411.9   78.44  412.52   74.51
  416.71   74.44  421.08   74.47  421.31   74.54  421.92   78.43  422.39   78.43
  434.11   85.89   465.3   85.83  476.62   84.91  476.85   85.42   495.9   86.01
  834.11   86.93
#Mann= 3 ,-1 , 0
       0     .99       0  400.01    .015       0  434.11     .99       0
#Block Obstruct= 2 , 0
       0                  434.11       0      86
Bank Sta=400.01,434.11
XS Rating Curve= 0
Exp/Cntr=.5,.3

Type RM Length L Ch R = 1 ,18310.25,72.64,72.63,72.65
BEGIN DESCRIPTION:
u/s of Westview Drive bridge
END DESCRIPTION:
XS GIS Cut Line= 2
     3061920.841    13851201.166     3061089.463     13851160.71
#Sta/Elev= 23
       0   84.36  114.35   84.17  232.81    85.8  282.29   85.42  328.14   85.22
   400.9   85.68  403.11   84.47  412.72   78.22  413.26   78.18  413.53   74.39
  414.16   74.16  422.54   74.25  422.65   74.41  423.66   78.21  423.99   78.34
  435.28   85.65  444.39   85.34  464.42   85.32  478.11   84.29  478.36    84.8
  526.11   84.94  620.98   85.41  832.36   85.81
#Mann= 3 ,-1 , 0
       0     .99       0   400.9    .015       0  435.28     .99       0
#XS Ineff= 2 , 0
       0   400.9   85.68  435.28       0   85.65
Permanent Ineff=
       F       F
Bank Sta=400.9,435.28
XS Rating Curve= 0
Exp/Cntr=.5,.3

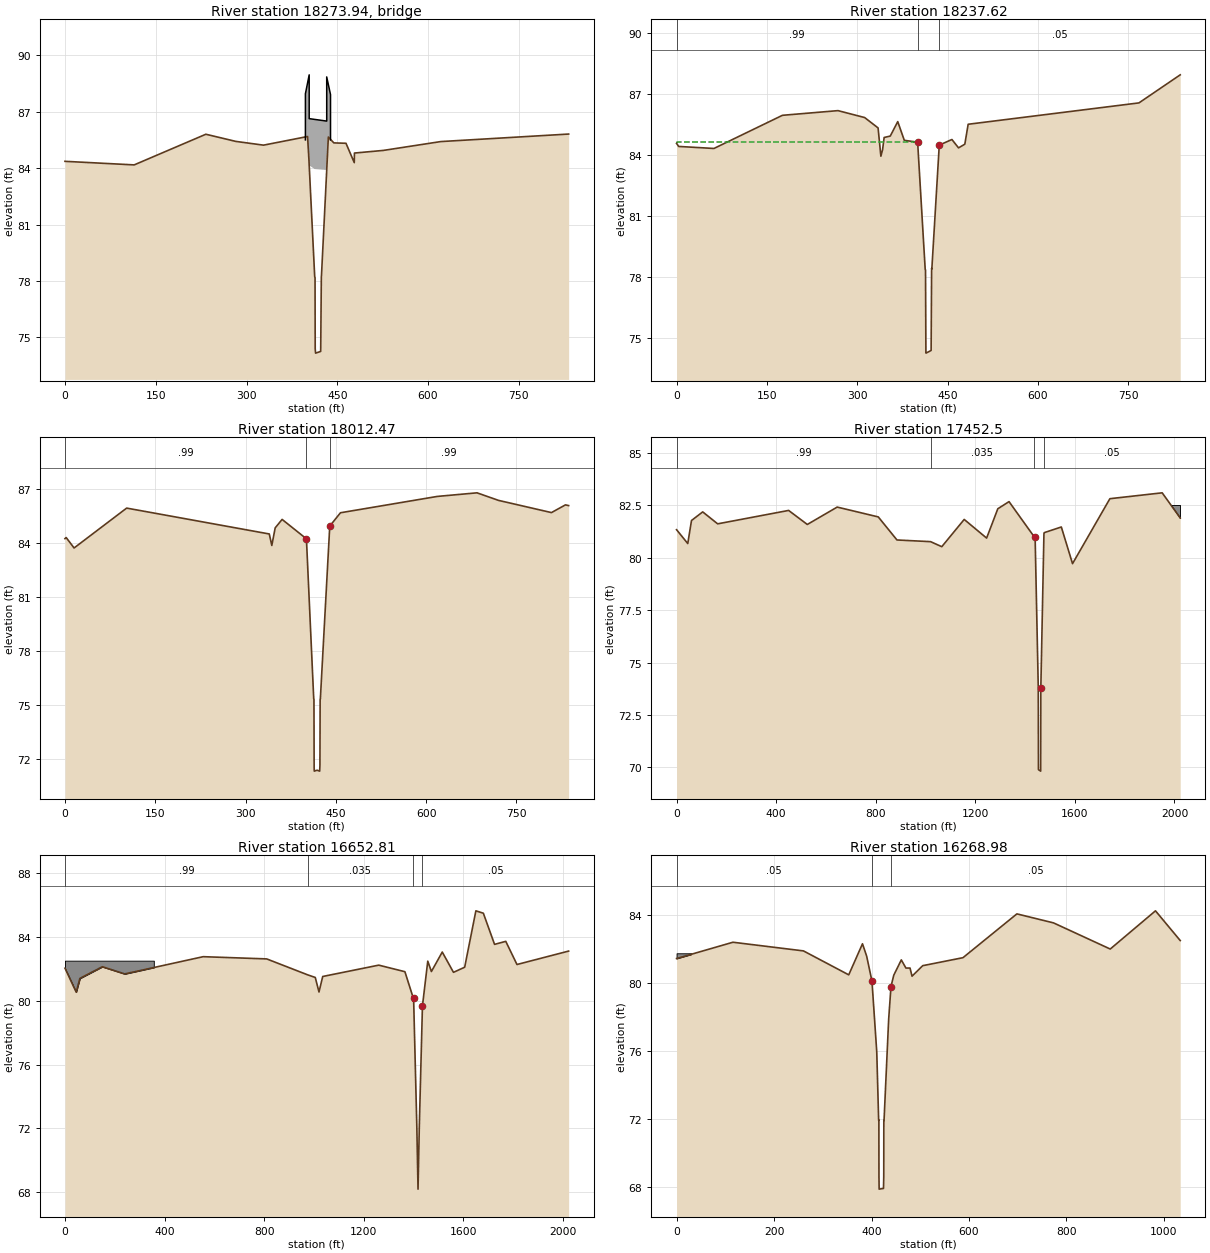
Type RM Length L Ch R = 3 ,18273.94,,,
BEGIN DESCRIPTION:
Westview Drive Bridge
END DESCRIPTION:
Bridge Culvert--1,0,-1,-1, 0
Deck Dist Width WeirC Skew NumUp NumDn MinLoCord MaxHiCord MaxSubmerge Is_Ogee
.63,60,2.6,0, 8, 8, 85.5, , .95, 0, 0,0,,
  397.33  397.33   403.6   403.6  432.54  432.54  438.83  438.83
    85.5   87.95   88.96   86.63    86.5   88.85   87.91    85.5
   83.97   83.97   83.97   83.97    83.9    83.9    83.9    83.9
  397.33  397.33   403.6   403.6  432.54  432.54  438.83  438.83
    85.5   87.95   88.96   86.63    86.5   88.85   87.91    85.5
   83.97   83.97   83.97   83.97    83.9    83.9    83.9    83.9
BR Coef=-1 , 0 , 0 ,, 0 ,,,.8,-1,,0,
WSPro=,,,, 1 ,,,, 0 ,,,, 0 ,,,,-1 ,-1 ,-1 , 0 , 0 , 0 , 0 , 0
BC Design=,, 0 ,, 0 ,,,,,,
BC HTab HWMax=85.81

Type RM Length L Ch R = 1 ,18237.62,225.15,225.15,225.19
BEGIN DESCRIPTION:
d/s of Westview Drive bridge
END DESCRIPTION:
XS GIS Cut Line= 2
      3061924.63     13851128.63     3061089.504    13851087.992
#Sta/Elev= 30
       0   84.57    3.46   84.42   62.08   84.32  175.74   85.95     268   86.18
  312.22   85.84  334.53   85.33  339.17   83.94  341.99   84.26  344.59   84.86
  354.77   84.93  367.16   85.64  378.07   84.72  400.19   84.63  412.76   78.37
  413.28   78.35  413.91   74.33  414.06   74.26  422.49   74.39  422.58   74.44
  423.39   78.43  423.78    78.4  436.11   84.49  436.45   84.49  457.09   84.76
  468.09   84.35  478.52   84.53  484.06   85.51  767.58   86.56  836.11   87.94
#Mann= 3 ,-1 , 0
       0     .99       0  400.19    .015       0  436.45     .05       0
#XS Ineff= 2 , 0
       0  400.19   84.63  436.11       0   84.49
Permanent Ineff=
       F       F
Bank Sta=400.19,436.11
XS Rating Curve= 0
Exp/Cntr=.5,.3

Type RM Length L Ch R = 1 ,18012.47,556,557,558
XS GIS Cut Line= 2
     3061936.374    13850903.786     3061100.491    13850863.112
#Sta/Elev= 26
       0   84.26    2.02   84.32   15.15   83.74  102.49   85.96  339.47   84.52
  343.67   83.88  349.29   84.86  360.79   85.33  401.19   84.25  413.31   75.36
   413.7   75.32  414.01    71.5  414.25   71.32  418.91   71.37  423.21   71.32
  423.62   71.62  423.98   75.31  424.31   75.32  439.97   84.96  457.75    85.7
   618.7   86.61  684.66   86.81  720.28   86.39  808.32   85.71  831.61   86.14
  836.87    86.1
#Mann= 3 ,-1 , 0
       0     .99       0  401.19    .015       0  439.97     .99       0
Bank Sta=401.19,439.97
XS Rating Curve= 0
Exp/Cntr=.3,.1

Type RM Length L Ch R = 1 ,17452.5 ,799.89,799.6901,778.76
BEGIN DESCRIPTION:
Floodplain mapping based on WSEL
END DESCRIPTION:
XS GIS Cut Line= 2
 3062492.748125613850373.5305941 3061128.521125613850302.3985942
#Sta/Elev= 30
       0   81.34   45.01   80.68   60.02   81.78  105.03   82.19  165.05   81.62
  450.13   82.26  525.15   81.59  645.19   82.42  810.24   81.95  885.26   80.85
  1020.3   80.77 1065.31   80.53 1155.34   81.83 1245.37   80.94 1290.38   82.34
 1335.39   82.68 1434.24   81.04 1438.27   81.01 1440.13   81.03 1452.85    73.8
 1453.56   69.89 1462.46   69.82 1463.12   73.78 1475.64   81.16 1476.78    81.2
 1545.45   81.47 1590.47   79.72 1740.51   82.82 1950.57    83.1 2023.05    81.9
#Mann= 4 ,-1 , 0
       0     .99       0  1020.3    .035       0 1434.24    .015       0
 1476.78     .05       0
#Block Obstruct= 1 ,-1
  1762.8 2023.05    82.5
Bank Sta=1438.27,1463.12
XS Rating Curve= 0
Exp/Cntr=.3,.1

Type RM Length L Ch R = 1 ,16652.81,384.08,383.83,369.35
BEGIN DESCRIPTION:
Floodplain mapping based on WSEL
END DESCRIPTION:
XS GIS Cut Line= 2
  3062532.08429513849574.8156168  3061167.85729513849503.6836168
#Sta/Elev= 30
       0   82.03   45.03   80.53   60.04   81.39   150.1   82.12  240.16   81.67
  555.37   82.75  810.54   82.61  975.65   81.61 1005.67   81.45 1020.68   80.54
 1035.69   81.51 1260.84   82.22 1365.91   81.81  1396.5   80.31 1400.86   80.15
 1413.77   72.13 1418.61    68.2 1423.79   72.13 1436.37   79.66 1457.76   82.47
 1472.38   81.82 1516.02   83.04 1561.05   81.77 1606.08   82.09 1651.11   85.62
 1681.13   85.47 1726.16   83.52 1771.19   83.71 1816.22   82.26 2023.81    83.1
#Mann= 4 ,-1 , 0
       0     .99       0  975.65    .035       0  1396.5    .015       0
 1436.37     .05       0
#Block Obstruct= 2 , 0
       0  356.97    82.5               0
Bank Sta=1400.86,1436.37
XS Rating Curve= 0
Exp/Cntr=.3,.1

Type RM Length L Ch R = 1 ,16268.98,36.58,35.65,80.09
BEGIN DESCRIPTION:
L
END DESCRIPTION:
XS GIS Cut Line= 3
     3062024.178    13849162.387      3061404.81    13849132.463
     3061179.368     13849478.95
#Sta/Elev= 30
       0   81.44   115.7    82.4  260.34   81.89  353.29   80.48  381.49   82.31
  390.06   81.58  400.94   80.11  410.78   75.94  414.68    71.9  415.11   71.93
  415.29   68.62  415.65   67.86   424.6    67.9  425.14    68.6  425.28    71.9
  425.71    71.9  435.18   77.85  439.96   79.79  445.69   80.46  461.16   81.36
  470.64   80.88  479.05   80.88  483.14    80.4  505.07   81.02  587.66   81.49
   698.3   84.07  773.45   83.54  889.83      82  982.69   84.25 1033.46    82.5
#Mann= 3 ,-1 , 0
       0     .05       0  400.94    .015       0  439.96     .05       0
#Block Obstruct= 1 ,-1
       0      30   81.75
Bank Sta=400.94,439.96
XS Rating Curve= 0
Exp/Cntr=.5,.3