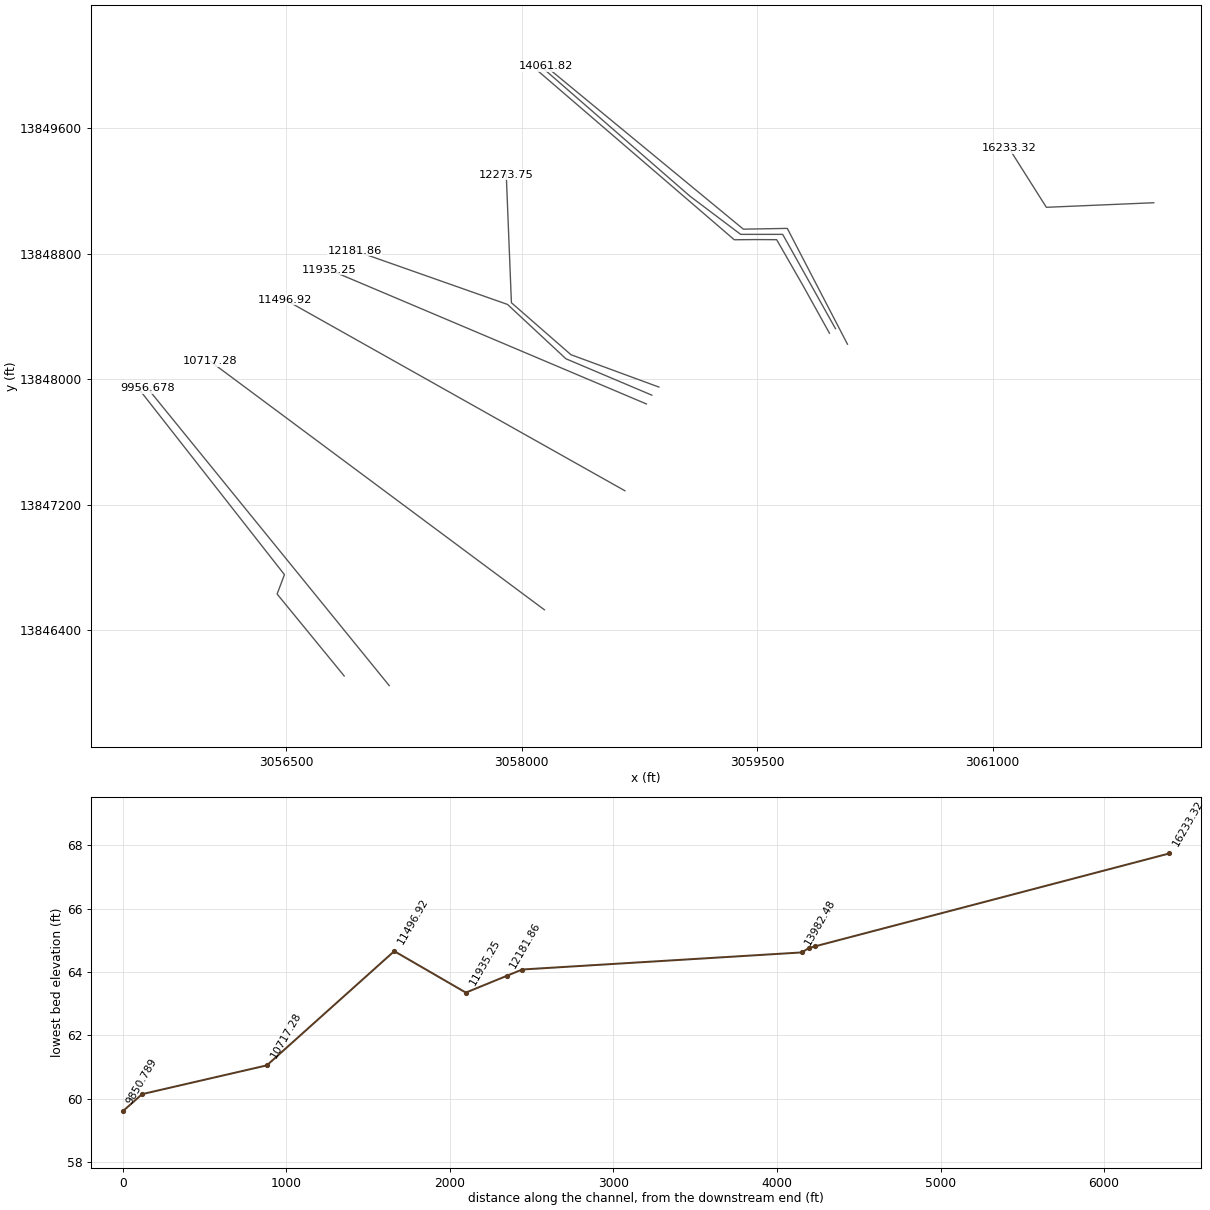
HEC-RAS study W156-00-00.prj: W156-00-00

--- W156-00-00.g02 (geometry) --- (continued)

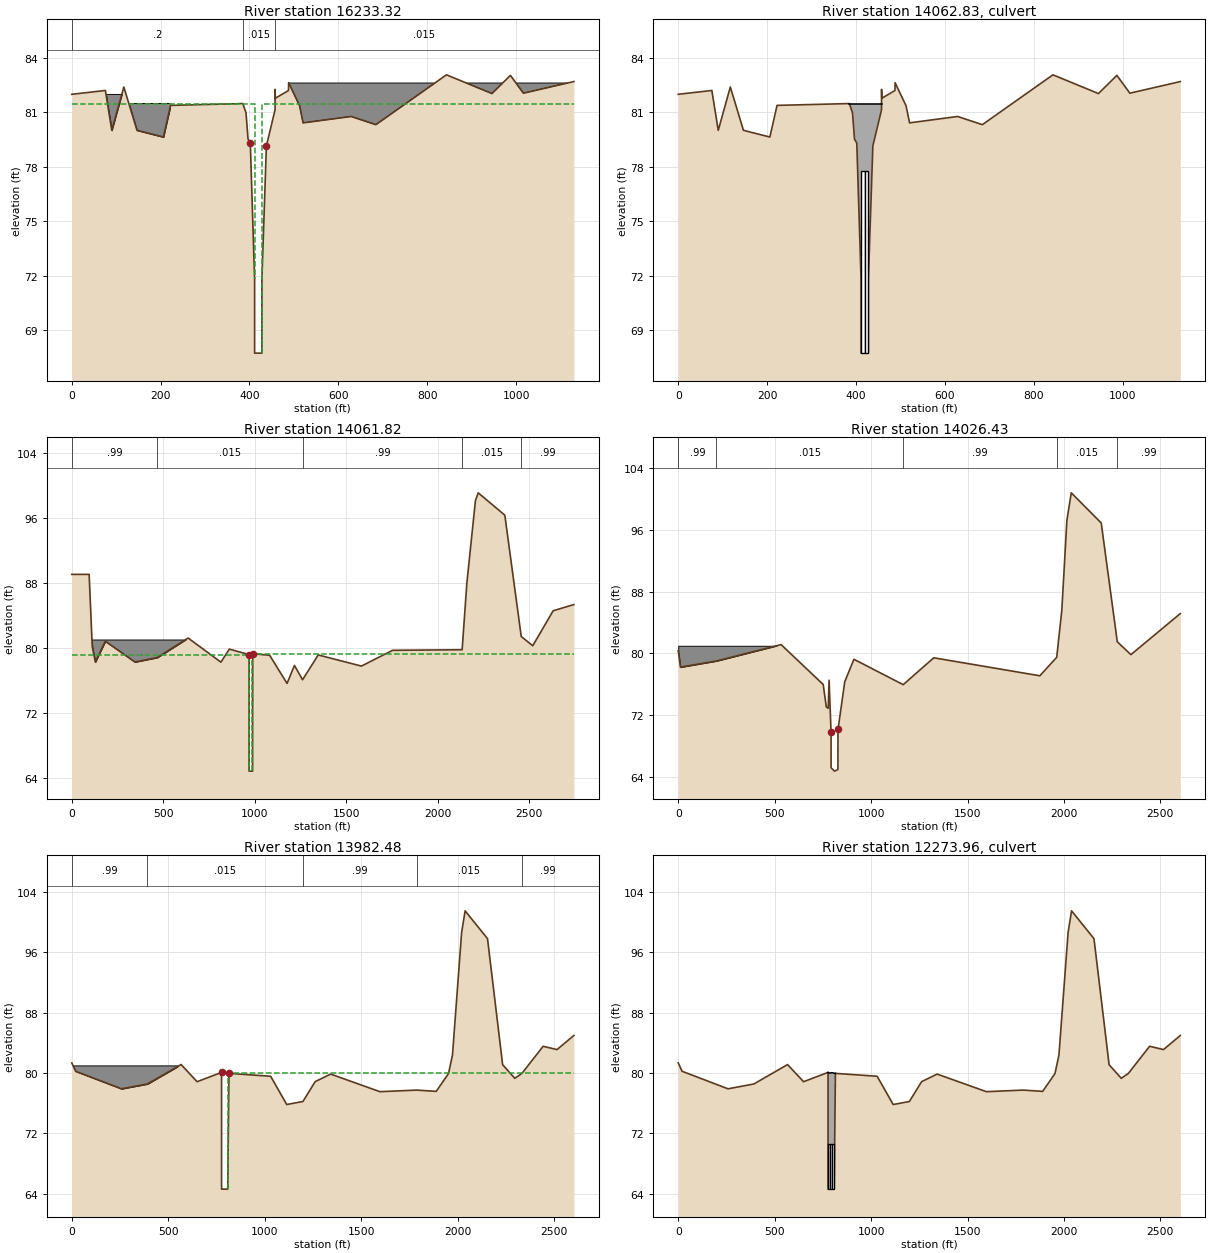
Type RM Length L Ch R = 1 ,16233.32,2278.05,2168.59,2067.65
BEGIN DESCRIPTION:
Cont./Expn. coeff. set at 0.3/0.5 to account for flow
END DESCRIPTION:
XS GIS Cut Line= 3
      3062026.11    13849124.322     3061342.324    13849095.302
     3061104.172    13849471.978
#Sta/Elev= 30
       0   81.98   75.65   82.19   90.06      80  117.21   82.38  146.77      80
  206.26   79.63   222.4   81.37  385.08   81.47  392.19   80.96  396.72   79.52
  401.87   79.29  411.53    71.8  411.53   67.75  427.87   67.75  427.87   71.76
  438.05   79.14  457.59   81.13  457.66   82.25  458.11   81.76  487.86   82.19
  488.06   82.62  512.75   81.35  520.71   80.41  628.88   80.76   684.5   80.31
  843.37   83.05  945.76   82.02  987.28   83.02 1016.52   82.04 1130.05   82.68
#Mann= 3 ,-1 , 0
       0      .2       0  385.08    .015       0  457.66    .015       0
#XS Ineff= 2 , 0
       0  411.53   81.47  427.87       0   81.47
Permanent Ineff=
       F       F
#Block Obstruct= 3 ,-1
   75.65     115      82     120  221.12    81.5  488.06 1130.05    82.6
Bank Sta=401.87,438.05
XS Rating Curve= 0
Exp/Cntr=.5,.3

Type RM Length L Ch R = 2 ,14062.83,,,
BEGIN DESCRIPTION:
2 - 8x10 culverts along Old Katy Road
END DESCRIPTION:
Bridge Culvert--1,0,-1,-1, 0
Deck Dist Width WeirC Skew NumUp NumDn MinLoCord MaxHiCord MaxSubmerge Is_Ogee
1,2150.7,2.6,0, 2, 5, 81.47, , .95, 0, 0,0,,
  385.08  457.59
   81.47   81.47
   67.75   67.75
  969.01  973.83  982.85  988.01  988.65
   79.14   79.05   79.28   79.24   79.25
   64.81   64.81   64.81   64.81   64.81
BR Coef=-1 , 0 , 0 ,, 0 ,,,.8,-1,,0,
WSPro=,,,, 1 ,,,, 0 ,,,, 0 ,,,,-1 ,-1 ,-1 , 0 , 0 , 0 , 0 , 0
Culvert=2,10,8,2150.7,.015,.7,1,8,1,67.75,415.53,64.81,974.01,Culvert #1  , 0 ,1
Culvert Bottom n=.015
Culvert Bottom Depth=10
Culvert=2,10,8,2150.7,.015,.7,1,8,1,67.75,423.87,64.81,983.01,Culvert #2  , 0 ,1
Culvert Bottom n=.015
Culvert Bottom Depth=10
BC Design=,, 0 ,, 0 ,,,,,,
BC HTab HWMax=83.05

Type RM Length L Ch R = 1 ,14061.82,39.55,35.44,50.86
XS GIS Cut Line= 4
     3060075.542    13848223.391     3059692.309    13848960.948
     3059412.458    13848956.038     3058153.088     13849994.59
#Sta/Elev= 30
       0   89.01   94.93   89.01  111.84   80.15  128.74   78.23  183.27   80.79
  345.45   78.23  467.26   78.78  635.86   81.18  815.17   78.21  860.88   79.82
  969.01   79.14  969.01   64.81  988.01   64.81  988.62   79.25 1081.16   79.06
 1176.45    75.6 1216.75   77.81 1261.16   76.05 1346.73    79.1 1582.71   77.73
 1752.84   79.67 2133.04   79.74 2158.89   87.95 2205.71   98.08 2220.94   99.04
 2366.35   96.29 2455.99   81.37 2518.85   80.23 2630.43   84.53 2743.43    85.3
#Mann= 5 ,-1 , 0
       0     .99       0  467.26    .015       0 1261.16     .99       0
 2133.04    .015       0 2455.99     .99       0
#XS Ineff= 2 , 0
       0  970.01   79.14  987.01       0   79.25
Permanent Ineff=
       F       F
#Block Obstruct= 2 , 0
       0  635.86      81 2455.99       0      82
Bank Sta=969.01,988.62
XS Rating Curve= 0
Exp/Cntr=.5,.3

Type RM Length L Ch R = 1 ,14026.43,49.33,44.05,31.4
BEGIN DESCRIPTION:
Transition from open channel to a culvert
END DESCRIPTION:
XS GIS Cut Line= 5
     3059999.179    13848322.356     3059662.851    13848922.898
     3059395.274    13848922.898     3059071.749    13849166.614
      3058134.72    13849982.345
#Sta/Elev= 30
       0   80.35   11.52   78.23  198.16   79.03  533.27   81.15  751.74   75.98
  767.59   73.08  777.45    72.9  782.15   76.54  792.34   69.82  792.46   69.79
  792.53   65.43  792.85   65.18  810.55   64.76  827.72   64.96  828.01   65.43
  828.18   69.99   828.6   70.18  863.35   76.33  910.97   79.25 1166.56   75.96
 1325.09   79.44 1875.02   77.11 1962.54   79.51 1988.97   85.62 2015.19   97.25
 2037.99  100.81 2193.22    96.9  2276.6   81.51 2347.14   79.85 2603.29   85.17
#Mann= 5 ,-1 , 0
       0     .99       0  198.16    .015       0 1166.56     .99       0
 1962.54    .015       0  2276.6     .99       0
#Block Obstruct= 2 , 0
       0  533.27      81  2276.6       0      82
Bank Sta=792.34,828.6
XS Rating Curve= 0
Exp/Cntr=.5,.3

Type RM Length L Ch R = 1 ,13982.48,1725.12,1709.5,1288.53
XS GIS Cut Line= 6
     3059960.764    13848293.544     3059792.697    13848596.065
      3059624.63    13848888.981     3059493.467    13848889.758
     3059354.769     13848888.53     3058104.108    13849963.977
#Sta/Elev= 30
       0   81.33   20.11   80.22  258.09    77.9  392.24   78.54  566.93   81.11
   649.7   78.84  776.63   80.07  776.63   64.62  808.63   64.62  814.94   79.95
  817.25   79.94 1031.21   79.56 1114.48   75.82  1198.4   76.22 1262.02   78.85
 1342.32   79.85 1597.65   77.52 1788.34   77.73 1889.58   77.56  1953.4   79.92
 1973.89   82.37 2021.22   98.58 2039.36  101.46 2155.49   97.78 2233.96   81.09
    2297   79.29  2333.9   79.94  2444.1   83.53  2515.8   83.09 2603.11   84.96
#Mann= 5 ,-1 , 0
       0     .99       0  392.24    .015       0  1198.4     .99       0
 1788.34    .015       0  2333.9     .99       0
#XS Ineff= 2 , 0
       0  776.63   80.07  808.63       0   79.95
Permanent Ineff=
       F       F
#Block Obstruct= 2 , 0
       0  547.71      81 2221.73       0      81
Bank Sta=776.63,817.25
XS Rating Curve= 0
Exp/Cntr=.5,.3

Type RM Length L Ch R = 2 ,12273.96,,,
BEGIN DESCRIPTION:
3-10x6 under I-10
END DESCRIPTION:
Bridge Culvert--1,0,-1,-1, 0
Deck Dist Width WeirC Skew NumUp NumDn MinLoCord MaxHiCord MaxSubmerge Is_Ogee
.2,1707.72,2.6,0, 6, 2, 79.95, , .95, 0, 0,0,,
  776.63   781.9  801.48  807.56  808.63  814.94
   80.07   79.99   80.03   79.95   79.95   79.95
   64.62   64.62   64.62   64.62   64.62   64.62
 1151.31 1185.28
   75.87   75.68
   64.08   64.08
BR Coef=-1 , 0 , 0 ,, 0 ,,,.8,-1,,0,
WSPro=,,,, 1 ,,,, 0 ,,,, 0 ,,,,-1 ,-1 ,-1 , 0 , 0 , 0 , 0 , 0
Culvert=2,6,10,1707.72,.015,.4,1,8,1,64.62,781.63,64.08,1156.31,Culvert #1  , 0 ,.2
Culvert Bottom n=.015
Culvert Bottom Depth=6
Culvert=2,6,10,1707.72,.015,.4,1,8,1,64.62,792.63,64.08,1167.31,Culvert #2  , 0 ,.2
Culvert Bottom n=.015
Culvert Bottom Depth=6
Culvert=2,6,10,1707.72,.015,.4,1,8,1,64.62,803.63,64.08,1178.31,Culvert #3  , 0 ,.2
Culvert Bottom n=.015
Culvert Bottom Depth=6
BC Design=,, 0 ,, 0 ,,,,,,
BC HTab HWMax=101.46

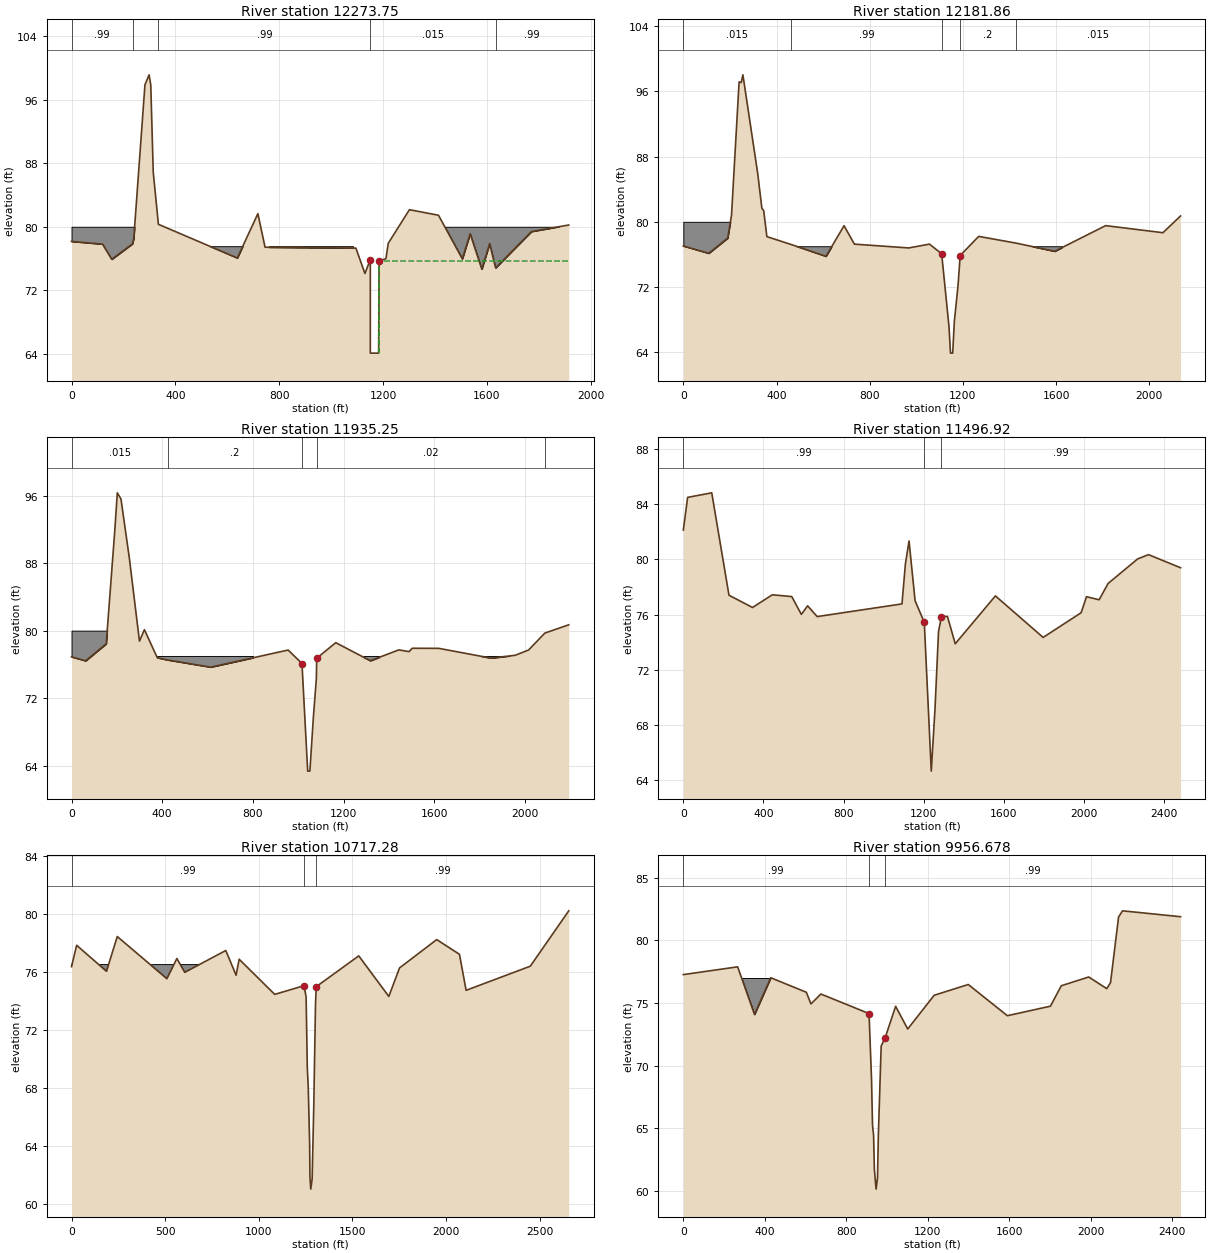
Type RM Length L Ch R = 1 ,12273.75,36.02,94.47,563.75
BEGIN DESCRIPTION:
Transition to a Junction Box
END DESCRIPTION:
XS GIS Cut Line= 4
     3058874.551    13847950.277      3058314.42    13848156.302
      3057935.14    13848487.439      3057902.37    13849302.316
#Sta/Elev= 30
       0   78.15  119.32   77.81  155.08    75.9  234.99   77.85  239.85   78.52
  282.94   97.89  298.92   99.14   305.3   97.87   314.9   86.86  334.73   80.31
  638.83   76.06  718.06   81.65  745.74   77.42 1095.72   77.31 1130.53   74.11
 1151.31   75.87 1151.31   64.08 1183.31   64.08 1185.28   75.68 1211.43   75.98
  1220.6   77.93 1301.95   82.15 1413.99   81.45 1505.83   75.95 1535.86   79.12
 1580.89   74.65 1610.92   77.87 1634.03   74.82 1772.11   79.39 1915.85   80.22
#Mann= 5 ,-1 , 0
       0     .99       0  234.99    .015       0  334.73     .99       0
 1151.31    .015       0 1634.03     .99       0
#XS Ineff= 2 , 0
       0 1151.31   75.87 1183.31       0   75.68
Permanent Ineff=
       F       F
#Block Obstruct= 4 ,-1
       0     245      80  505.02  679.78   77.55  760.86 1084.96   77.55
 1413.99    1915      80
Bank Sta=1151.31,1185.28
XS Rating Curve= 0
Exp/Cntr=.5,.3

Type RM Length L Ch R = 1 ,12181.86,123.97,250.23,214.35
BEGIN DESCRIPTION:
K - Transition to a Junction Box
END DESCRIPTION:
XS GIS Cut Line= 4
     3058829.483    13847898.771     3058282.229    13848130.549
     3057910.338    13848476.598     3056936.627    13848819.445
#Sta/Elev= 30
       0   77.03  109.12   76.13  190.57      78  206.86   80.81  239.44   97.17
  248.54   97.09  255.73   98.04  319.38   85.93  337.18   81.66  344.99   81.38
  358.66   78.18  464.32    77.2   612.3   75.76  690.05   79.52  734.35   77.26
  967.71   76.79 1056.58   77.26 1109.01   76.08 1140.63    67.1 1146.92   63.88
 1156.44   63.88  1163.5   67.79 1179.26   72.15 1188.53   75.86 1268.04   78.21
 1427.18   77.39 1594.27   76.38    1813   79.53    2059   78.66 2134.61   80.72
#Mann= 5 ,-1 , 0
       0    .015       0  464.32     .99       0 1109.01    .015       0
 1188.53      .2       0 1427.18    .015       0
#Block Obstruct= 3 ,-1
       0     210      80  464.32  635.73      77    1500    1625      77
Bank Sta=1109.01,1188.53
XS Rating Curve= 0
Exp/Cntr=.3,.1

Type RM Length L Ch R = 1 ,11935.25,464.74,437.75,380.05
XS GIS Cut Line= 2
     3058794.892    13847842.772      3056775.67    13848697.118
#Sta/Elev= 30
       0   76.89   62.39   76.42  152.98   78.44  190.54   91.77  201.84   96.33
  218.13    95.6  255.13   88.56  299.56   78.75  321.45   80.11  378.37   76.78
  424.32   76.52  613.69   75.67  955.26    77.7 1016.18    76.1 1041.35   63.35
 1051.04   63.36 1066.56   69.79 1079.53   74.29 1081.19   76.73 1165.15   78.57
 1317.52   76.43 1443.36   77.72 1488.54   77.51 1502.28   77.91  1619.5    77.9
 1849.91   76.74 1956.65   77.08 2015.26    77.7 2087.17   79.71 2192.52   80.69
#Mann= 5 ,-1 , 0
       0    .015       0  424.32      .2       0 1016.18    .015       0
 1081.19     .02       0 2087.17    .015       0
#Block Obstruct= 4 ,-1
       0     160      80  377.25     800      77    1288  1357.5      77
    1806    1957      77
Bank Sta=1016.18,1081.19
XS Rating Curve= 0
Exp/Cntr=.3,.1

Type RM Length L Ch R = 1 ,11496.92,799.22,779.01,707.19
XS GIS Cut Line= 2
       3058657.7    13847290.024     3056493.626    13848506.895
#Sta/Elev= 30
       0   82.13   21.45    84.5  141.91   84.83  227.95   77.41  345.41   76.52
   444.5   77.44   541.5   77.31  589.34   76.02  620.66   76.64  668.41   75.86
 1091.74   76.78 1109.08    79.7 1127.05   81.34 1157.23   77.01 1203.14   75.44
 1238.01   64.66 1256.67   69.17 1274.27   74.78 1289.01   75.86 1318.87   75.87
 1357.69   73.89 1558.32   77.36 1796.63   74.35 1986.27   76.14 2013.24    77.3
 2076.19   77.08 2120.92   78.26 2268.52   80.04  2322.6   80.35 2482.74    79.4
#Mann= 3 ,-1 , 0
       0     .99       0 1203.14    .015       0 1289.01     .99       0
Bank Sta=1203.14,1289.01
XS Rating Curve= 0
Exp/Cntr=.3,.1

Type RM Length L Ch R = 1 ,10717.28,837.44,762.81,667.78
BEGIN DESCRIPTION:
Floodplain mapping based on WSEL
END DESCRIPTION:
XS GIS Cut Line= 2
     3058145.333    13846531.587     3056014.968    13848115.878
#Sta/Elev= 30
       0   76.36    27.3   77.83  186.68   76.04  244.25   78.43  509.14   75.53
  562.45   76.92  604.74   75.97   823.7   77.47  878.65   75.77  895.08   76.87
 1084.95   74.45  1241.7   75.05 1252.54   74.27 1259.03   69.38 1263.86    68.1
 1271.34   64.22 1272.97   61.92 1277.34   61.05 1284.68   61.73 1293.35    66.7
 1302.71   73.79  1306.7   74.98 1533.63    77.1 1694.27   74.31 1751.29   76.27
 1949.94   78.22 2071.27   77.21 2106.88   74.73 2449.56   76.39 2654.89    80.2
#Mann= 3 ,-1 , 0
       0     .99       0  1241.7    .035       0  1306.7     .99       0
#Block Obstruct= 2 , 0
       0  818.21    76.5               0
Bank Sta=1241.7,1306.7
XS Rating Curve= 0
Exp/Cntr=.3,.1

Type RM Length L Ch R = 1 ,9956.678,185.55,117.85,66.61
BEGIN DESCRIPTION:
J
END DESCRIPTION:
XS GIS Cut Line= 2
      3057156.87    13846048.837     3055616.779    13847943.839
#Sta/Elev= 30
       0   77.26   266.8   77.88  349.51   74.08  429.37   77.01  604.15   75.85
  626.75   74.92  675.63   75.71   912.1   74.15  924.23   68.94  929.21   65.22
  934.37   64.45  938.28    61.7  946.62   60.14  953.72   61.04  957.74   64.42
  971.64   71.56  991.26   72.22 1042.61   74.73 1102.02   72.92 1231.87   75.61
 1399.25   76.47 1591.39   73.98 1802.97   74.74 1856.23   76.37 1990.87   77.07
 2079.58   76.14 2098.01   76.62 2137.53   81.86 2157.07   82.35 2441.91   81.88
#Mann= 3 ,-1 , 0
       0     .99       0   912.1    .035       0  991.26     .99       0
#Block Obstruct= 1 ,-1
   266.8  428.68   76.99
Bank Sta=912.1,991.26
XS Rating Curve= 0
Exp/Cntr=.5,.3

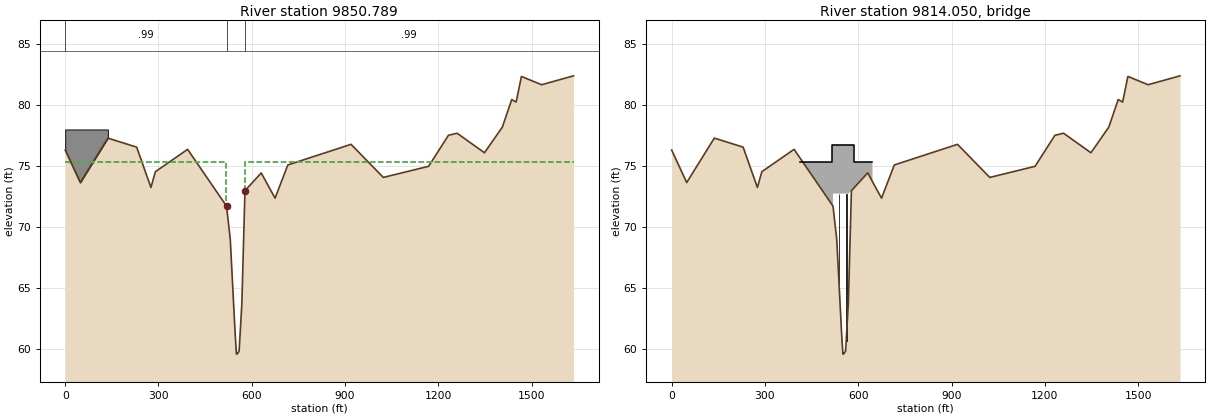
Type RM Length L Ch R = 1 ,9850.789,62.55,72.28,69.2
BEGIN DESCRIPTION:
u/s face of Brittmore Dr. Bridge
END DESCRIPTION:
XS GIS Cut Line= 4
        3056870.    13846110.357     3056442.831    13846632.044
     3056489.562    13846755.545     3055560.409    13847940.469
#Sta/Elev= 30
       0   76.31  48.401   73.65 137.108   77.29 229.831   76.55 275.715   73.25
 290.062   74.54 393.682   76.37 518.882   71.72 530.931   68.99  546.53   61.31
 550.681   59.61 552.823    59.6 559.336   59.85  568.14   63.73  578.13   72.98
 630.428   74.44 674.955   72.37 716.002   75.09 919.317   76.781023.127   74.07
1168.756   74.981232.607   77.52 1260.39   77.69 1348.46   76.09 1405.94   78.19
1436.183   80.451450.326   80.241467.324   82.341532.286   81.661634.895   82.39
#Mann= 3 ,-1 , 0
       0     .99       0 518.882    .035       0  578.13     .99       0
#XS Ineff= 2 , 0
       0  518.43   75.35  578.13       0   75.35
Permanent Ineff=
       F       F
#Block Obstruct= 1 ,-1
       0 137.108      78
Bank Sta=518.882,578.13
XS Rating Curve= 0
Skew Angle= 45
Exp/Cntr=.5,.3

Type RM Length L Ch R = 3 ,9814.050,,,
BEGIN DESCRIPTION:
Brittmore Dr. Bridge
END DESCRIPTION:
Bridge Culvert--1,0,-1,-1, 0
Deck Dist Width WeirC Skew NumUp NumDn MinLoCord MaxHiCord MaxSubmerge Is_Ogee
.01,60,2.6,45, 11, 11, 75.35, , .95, 0, 0,0,,
 412.547 514.703 514.986 514.986 518.656 518.656 580.612 580.612 584.926 584.926
 645.878
   75.35   75.35   75.35   76.75   76.75   76.75   76.75   76.75   76.75   75.35
   75.35
   66.25   66.25   66.25   66.25   66.25   72.75   72.75   66.25   66.25   66.25
   66.25
 410.072 452.329 512.525 512.525 516.372 516.372 578.463 578.463  582.79  582.79
 636.375
   75.35   75.35   75.35   76.75   76.75   76.75   76.75   76.75   76.75   75.35
   75.35
   66.25   66.25   66.25   66.25   66.25   72.75   72.75   66.25   66.25   66.25
   66.25
Pier Skew, UpSta & Num, DnSta & Num=  ,538.122, 4 ,535.853, 4 , 3 , 3 , 0 ,,
    1.33    1.33     2.6     2.6
      60   73.92   73.92    76.5
    1.33    1.33     2.6     2.6
      60   73.92   73.92    76.5
Pier Skew, UpSta & Num, DnSta & Num=  ,561.266, 4 ,558.968, 4 , 3 , 3 , 0 ,,
    1.33    1.33     2.6     2.6
      60   73.92   73.92    76.5
    1.33    1.33     2.6     2.6
      60   73.92   73.92    76.5
BR Coef=-1 , 1 , 1 ,1.25, 0 ,,,.8,-1,2,0,
WSPro=,,,, 1 ,,,, 0 ,,,, 0 ,,,,-1 ,-1 ,-1 , 0 , 0 , 0 , 0 , 0
BC Design=,, 0 ,, 0 ,,,,,,
BC HTab HWMax=82.39