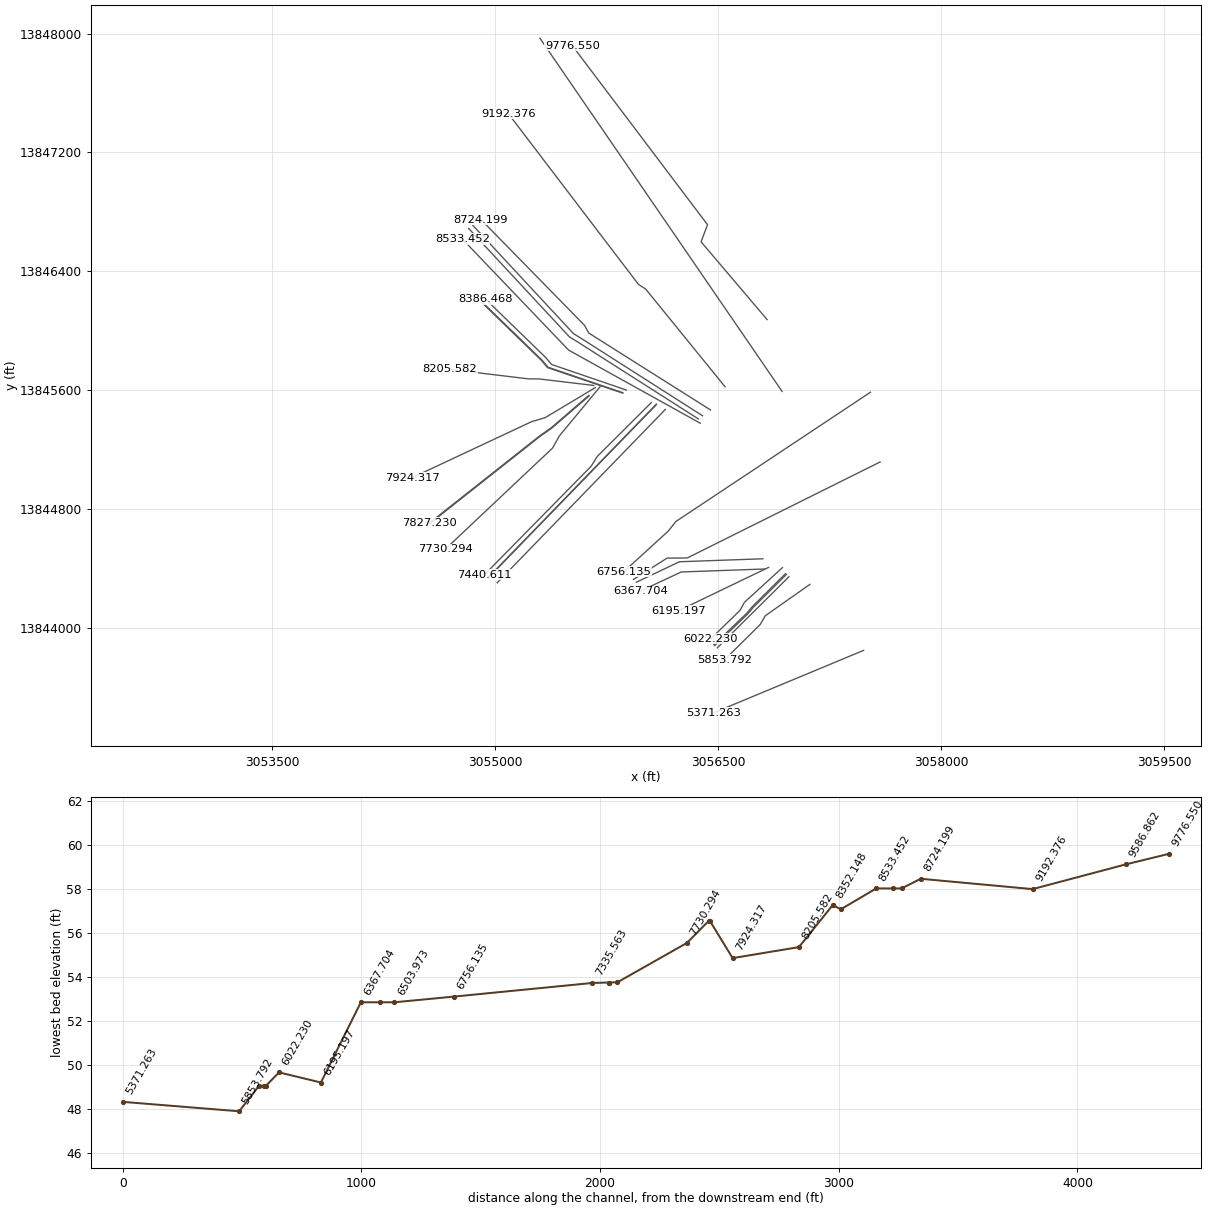
HEC-RAS study W156-00-00.prj: W156-00-00

--- W156-00-00.g02 (geometry) --- (continued)

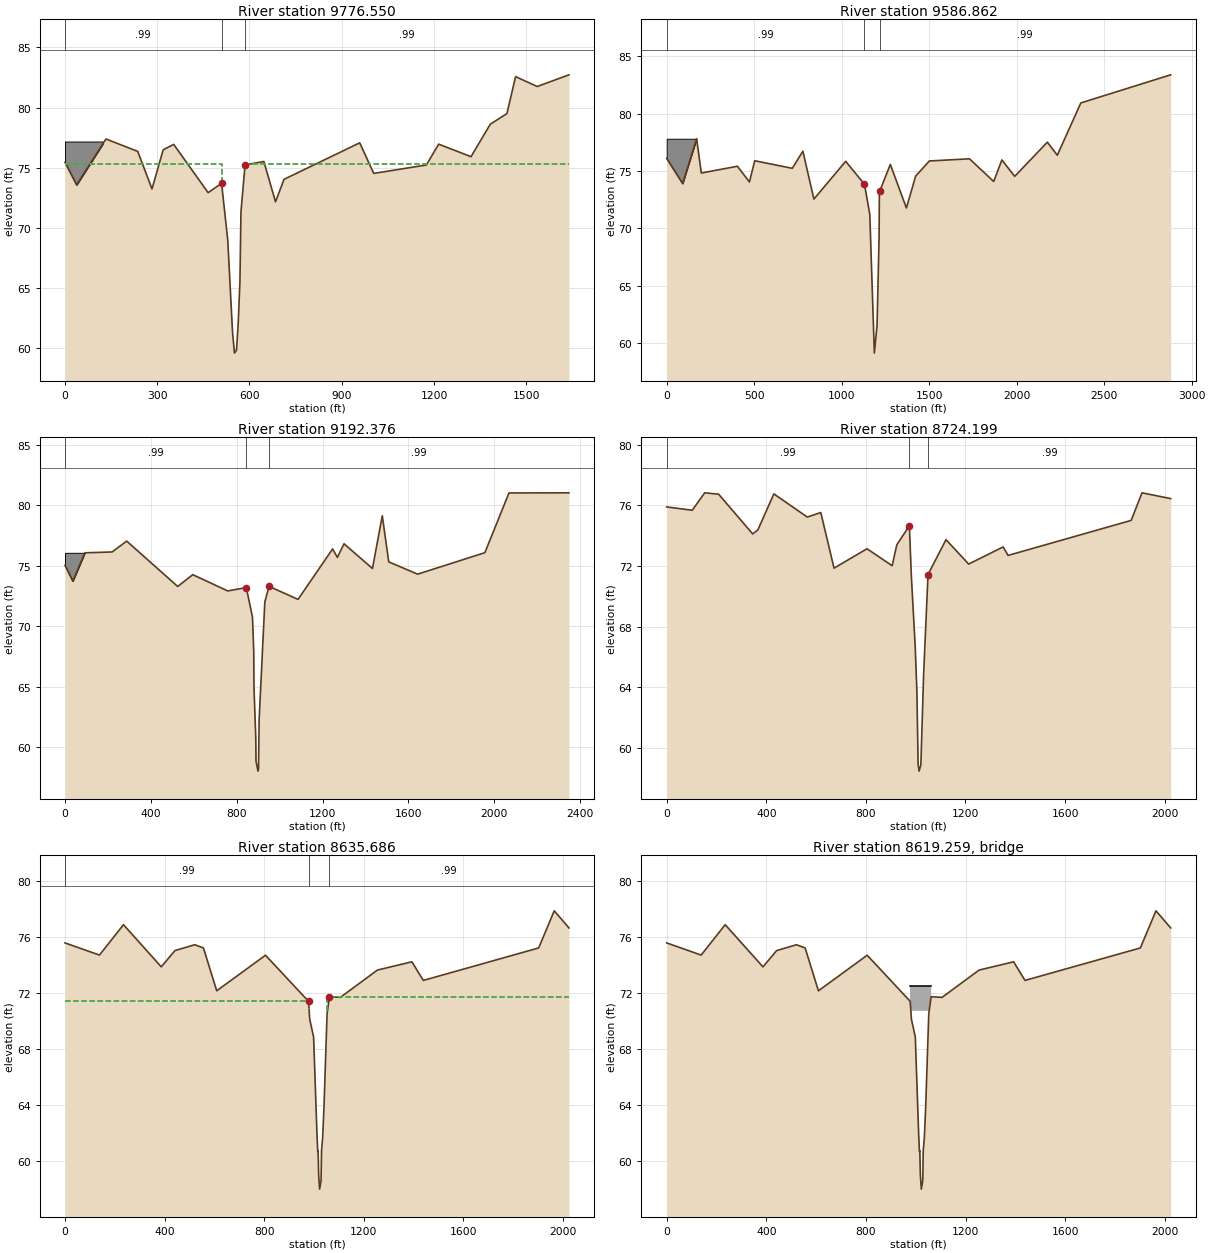
Type RM Length L Ch R = 1 ,9776.550,143.92,180.78,207.37
BEGIN DESCRIPTION:
d/s face of Brittmore Dr. Bridge
END DESCRIPTION:
XS GIS Cut Line= 4
     3056827.828    13846076.093      3056383.47    13846599.169
      3056426.99    13846714.186     3055517.766    13847918.054
#Sta/Elev= 30
       0   75.45  37.802   73.57 133.212   77.39 236.534   76.36 282.949   73.24
 319.336   76.49  353.61   76.94  465.51   72.93 509.272   73.71  529.34   68.99
 544.939   61.31 551.233    59.6 557.745   59.85 563.084   61.95 568.918   65.51
 572.276   71.34 585.619   75.24 646.812   75.52 684.614   72.17 712.368   74.04
 958.568   77.071004.021   74.531175.254   75.231215.205   76.961320.451   75.92
1383.235   78.621437.237    79.51465.394   82.57 1535.73   81.751639.038   82.72
#Mann= 3 ,-1 , 0
       0     .99       0 509.272    .035       0 585.619     .99       0
#XS Ineff= 2 , 0
       0 509.272   75.35 585.619       0   75.35
Permanent Ineff=
       F       F
#Block Obstruct= 1 ,-1
       0 122.987   77.18
Bank Sta=509.272,585.619
XS Rating Curve= 0
Skew Angle= 45
Exp/Cntr=.5,.3

Type RM Length L Ch R = 1 ,9586.862,350.79,392.38,407.52
XS GIS Cut Line= 2
     3056928.602    13845592.565     3055300.037    13847968.066
#Sta/Elev= 30
       0   76.09   91.01    73.9  170.97   77.81  197.92   74.82  404.13   75.41
  472.93   74.04  503.22   75.89  717.71   75.23  778.32   76.72  841.34   72.55
  1022.9   75.84 1130.43   73.84 1160.75   71.21 1186.71   59.12 1202.13   61.53
 1213.71   69.16 1215.44   72.92 1216.94   73.21 1277.98   75.57 1370.03   71.77
  1422.7   74.55 1501.16   75.87 1730.24   76.06 1868.83   74.08 1915.48   75.96
 1988.87   74.53 2175.42   77.51 2232.27   76.37 2366.83   80.93 2880.14   83.38
#Mann= 3 ,-1 , 0
       0     .99       0 1130.43    .035       0 1216.94     .99       0
#Block Obstruct= 1 ,-1
       0  170.97   77.81
Bank Sta=1130.43,1216.94
XS Rating Curve= 0
Exp/Cntr=.3,.1

Type RM Length L Ch R = 1 ,9192.376,413.51,468.57,491.47
XS GIS Cut Line= 4
     3056544.697    13845624.447     3056011.924    13846280.364
     3055961.904    13846313.511     3055087.316    13847461.276
#Sta/Elev= 30
       0   75.04   36.31   73.73    92.7   76.08  219.59   76.15  287.49   77.05
  525.26   73.29  595.21   74.27  758.06   72.92  844.71    73.2  873.49   70.75
  879.49   67.85  880.49   64.92  888.88   60.75  889.91   58.82  899.27   57.99
   901.7    58.2  904.49   62.25  930.98      72  950.59    73.3 1085.67   72.22
 1246.78    76.4 1269.08    75.7 1299.96   76.83 1432.47   74.78 1478.26   79.15
 1508.34   75.33 1642.87   74.31 1956.14   76.09 2068.57   81.04 2348.04   81.05
#Mann= 3 ,-1 , 0
       0     .99       0  844.71    .035       0  950.59     .99       0
#Block Obstruct= 1 ,-1
       0    92.7   76.08
Bank Sta=844.71,950.59
XS Rating Curve= 0
Exp/Cntr=.3,.1

Type RM Length L Ch R = 1 ,8724.199,64.36,80.36,85.44
BEGIN DESCRIPTION:
I
END DESCRIPTION:
XS GIS Cut Line= 4
     3056447.313    13845468.196      3055627.84    13845985.839
     3055600.079    13846036.978      3054902.71    13846749.338
#Sta/Elev= 30
       0   75.89  102.59   75.67  152.82   76.82  208.58   76.73  345.35   74.11
  366.19   74.37  430.59   76.75  564.83   75.22  618.97   75.52  672.19   71.85
   804.7   73.13  905.64   72.01  924.29   73.39  974.62   74.64  974.83   74.65
  982.69   71.34  998.01   66.75 1005.01   63.75 1010.01   58.89 1013.99   58.46
 1020.96   58.88 1032.01   64.85 1049.72   71.43 1121.91   73.73 1212.96   72.12
 1351.48   73.25 1371.23   72.69 1865.63      75 1909.25   76.82 2024.35   76.44
#Mann= 3 ,-1 , 0
       0     .99       0  974.83    .035       0 1049.72     .99       0
Bank Sta=974.62,1049.72
XS Rating Curve= 0
Exp/Cntr=.5,.3

Type RM Length L Ch R = 1 ,8635.686,36.39,34.22,34.91
BEGIN DESCRIPTION:
u/s face of Rummel Cr. Dr. Bridge
END DESCRIPTION:
XS GIS Cut Line= 4
     3056392.771    13845429.739     3055577.139    13845949.879
      3055525.85    13845981.368     3054847.524    13846711.117
#Sta/Elev= 30
       0    75.6  138.47   74.73   234.9    76.9  386.64   73.89  441.57   75.05
  521.17   75.47  555.97   75.24  609.34   72.18  805.18   74.72  977.91   71.43
  982.78   70.15  998.41   68.88 1011.84   61.97 1014.96   60.71 1016.46   60.76
 1018.75   58.99 1022.54   58.02 1028.35   58.63 1030.21   60.76 1034.75   61.71
 1039.93   63.83 1052.49   70.54 1061.97   71.76 1105.77   71.71 1254.54   73.66
 1393.23   74.25 1438.87   72.92 1902.23   75.24 1964.72   77.89 2023.88   76.67
#Mann= 3 ,-1 , 0
       0     .99       0  977.91    .035       0 1061.97     .99       0
#XS Ineff= 2 , 0
       0  980.13   71.48 1054.12       0   71.76
Permanent Ineff=
       F       F
Bank Sta=977.91,1061.97
XS Rating Curve= 0
Exp/Cntr=.5,.3

Type RM Length L Ch R = 3 ,8619.259,,,
BEGIN DESCRIPTION:
Rummel Cr. Dr. Bridge
END DESCRIPTION:
Bridge Culvert--1,0,-1,-1, 0
Deck Dist Width WeirC Skew NumUp NumDn MinLoCord MaxHiCord MaxSubmerge Is_Ogee
.01,34.2,2.6,0, 2, 2, 72.55, , .95, 0, 0,0,,
     977    1062
   72.55   72.55
   70.75   70.75
     977    1062
   72.55   72.55
   70.75   70.75
BR Coef=-1 , 0 , 0 ,, 0 ,,,.8,-1,,0,
WSPro=,,,, 1 ,,,, 0 ,,,, 0 ,,,,-1 ,-1 ,-1 , 0 , 0 , 0 , 0 , 0
BC Design=,, 0 ,, 0 ,,,,,,
BC HTab HWMax=77.91

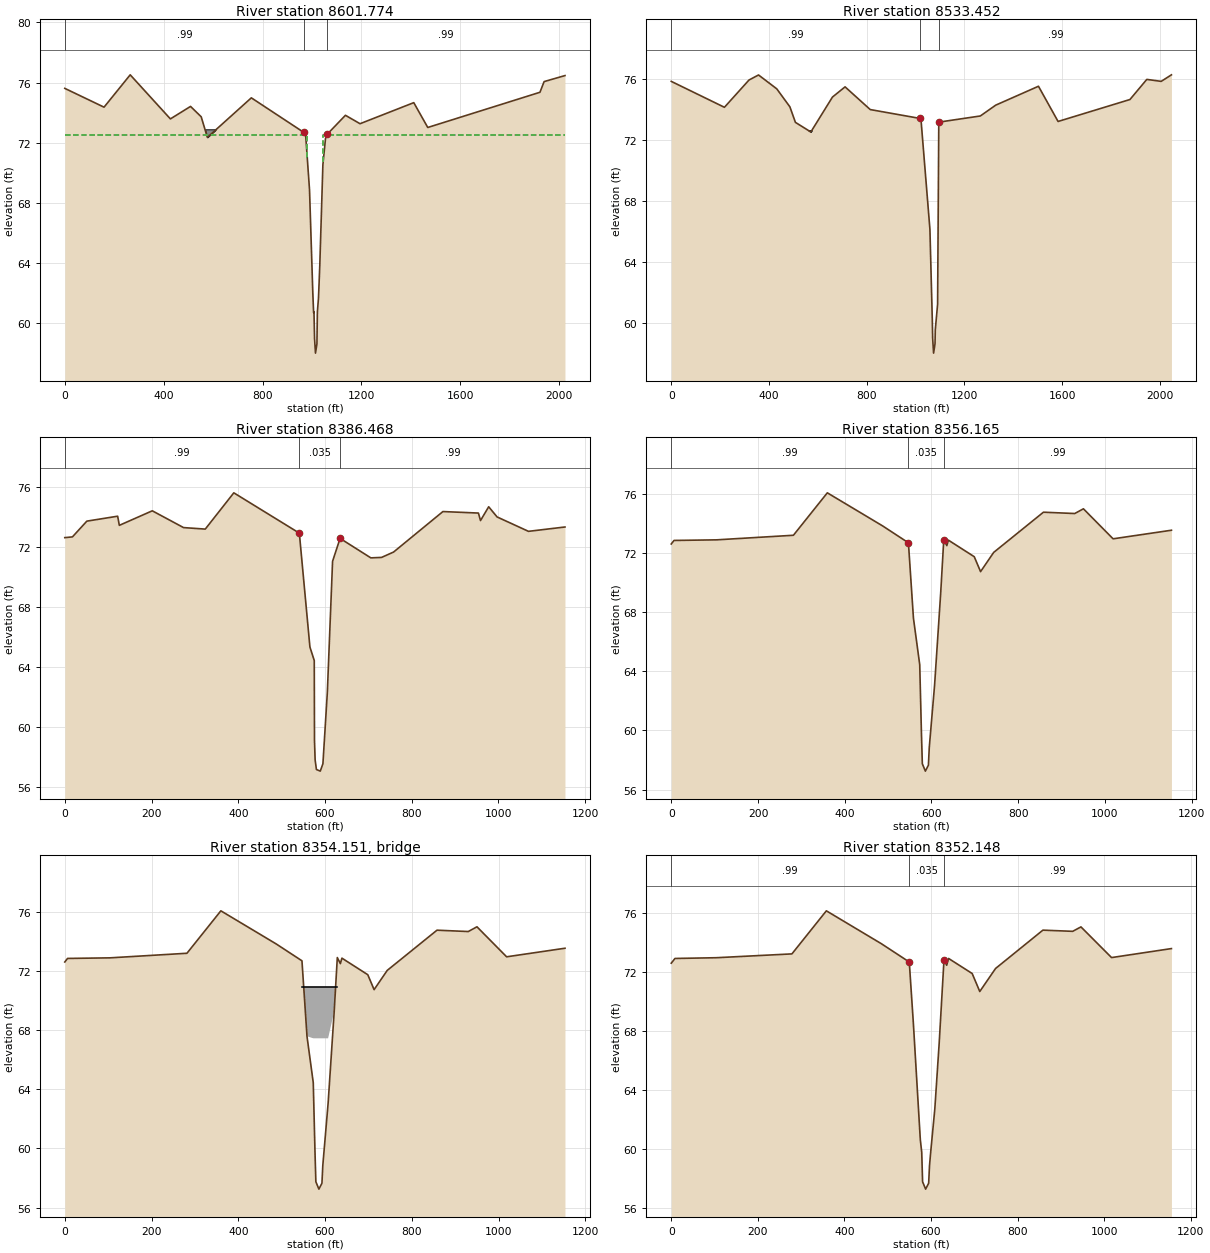
Type RM Length L Ch R = 1 ,8601.774,73.25,72.13,69.11
BEGIN DESCRIPTION:
d/s face of Rummel Cr. Dr. Bridge
END DESCRIPTION:
XS GIS Cut Line= 4
     3056365.464    13845407.899     3055549.832    13845928.038
     3055498.543    13845959.528     3054820.217    13846689.276
#Sta/Elev= 30
       0   75.62  158.79   74.37  264.69   76.52  427.26   73.59   508.8   74.42
  551.93   73.73  576.96   72.36  754.81   74.99  967.37   72.69  974.94   72.44
  990.24   68.88 1003.67   61.97 1006.79   60.71 1008.29   60.76 1010.58   58.99
 1014.37   58.02 1020.18   58.63 1022.04   60.76 1026.58   61.71 1031.76   63.83
 1044.32   70.54 1054.86   72.28 1061.26   72.56 1135.56   73.83 1194.64   73.27
 1412.09   74.67 1468.69   73.02 1922.67   75.36 1939.44   76.07 2023.87   76.47
#Mann= 3 ,-1 , 0
       0     .99       0  967.37    .035       0 1061.26     .99       0
#XS Ineff= 2 , 0
       0  981.51   72.55 1045.59       0   72.55
Permanent Ineff=
       F       F
#Block Obstruct= 2 , 0
       0     610    72.9               0
Bank Sta=967.37,1061.26
XS Rating Curve= 0
Exp/Cntr=.5,.3

Type RM Length L Ch R = 1 ,8533.452,118.18,148.42,154.48
XS GIS Cut Line= 4
     3056378.382    13845379.025      3055492.56     13845870.99
     3055454.124    13845911.233     3054778.008    13846617.835
#Sta/Elev= 30
       0   75.85  217.56   74.15  318.21   75.94  357.17   76.27  431.81   75.36
  485.43   74.18  508.12   73.16  571.22   72.53  659.64   74.82   711.3   75.49
  814.31      74 1017.64   73.42 1022.45   73.25  1058.5   66.15 1068.26   60.19
 1069.74   58.99 1073.53   58.02 1079.34   58.63  1080.5   59.55 1089.97   61.23
 1094.74   73.05 1096.81   73.18 1264.83   73.58 1327.79   74.29 1502.73   75.53
 1582.95   73.22 1877.14   74.66 1946.07   75.98 2004.92   75.85 2046.88   76.28
#Mann= 3 ,-1 , 0
       0     .99       0 1017.64    .035       0 1096.81     .99       0
#Block Obstruct= 2 , 0
       0     575   72.65               0
Bank Sta=1017.64,1096.81
XS Rating Curve= 0
Exp/Cntr=.3,.1

Type RM Length L Ch R = 1 ,8386.468,32.09,30.54,29.93
BEGIN DESCRIPTION:
H
H
END DESCRIPTION:
XS GIS Cut Line= 4
     3055880.712    13845602.335     3055377.745    13845774.417
     3055339.677    13845819.936     3054936.008    13846211.634
#Sta/Elev= 30
       0   72.65   17.66    72.7   50.83   73.75  121.88   74.08  125.77   73.47
  201.72   74.44  273.87   73.32  323.93   73.22  389.75   75.64  540.86   72.95
  565.26   65.35  575.26   64.45   575.8    59.1  577.26   57.82  580.24   57.18
  589.12   57.07  595.21   57.56  605.44   62.33  617.49   71.07  634.78    72.6
  705.71    71.3  730.47   71.33  758.25   71.69  871.94   74.39   953.8   74.29
  958.66   73.79  977.49   74.71  996.88   74.03 1069.24   73.07  1153.4   73.36
#Mann= 3 ,-1 , 0
       0     .99       0  540.86    .035       0  634.78     .99       0
Bank Sta=540.86,634.78
XS Rating Curve= 0
Exp/Cntr=.5,.3

Type RM Length L Ch R = 1 ,8356.165,3.76,4.05,3.97
BEGIN DESCRIPTION:
u/s of 42" steel pipeline # 2
END DESCRIPTION:
XS GIS Cut Line= 4
     3055856.795    13845584.013     3055353.912    13845755.834
     3055315.845    13845801.354     3054912.175    13846193.051
#Sta/Elev= 27
       0   72.61     6.3   72.85  104.21   72.89  281.63    73.2  359.84   76.07
  487.47   73.83  546.82   72.69   558.4   67.59  572.88   64.45  576.88   59.75
  578.88   57.75  585.88   57.25  592.88   57.65  594.88   58.85  607.11   63.05
   621.2   69.28  628.33   72.91  635.35    72.5  638.94   72.87  698.59   71.75
  713.17   70.74  743.38   72.04  858.13   74.76   930.3   74.67  950.32   74.99
 1018.69   72.96 1153.24   73.54
#Mann= 3 ,-1 , 0
       0     .99       0  546.82    .035       0  628.33     .99       0
Bank Sta=546.82,628.33
XS Rating Curve= 0
Exp/Cntr=.5,.3

Type RM Length L Ch R = 3 ,8354.151,,,
BEGIN DESCRIPTION:
42" steel pipeline # 2
END DESCRIPTION:
Bridge Culvert--1,0,-1,-1, 0
Deck Dist Width WeirC Skew NumUp NumDn MinLoCord MaxHiCord MaxSubmerge Is_Ogee
.01,3.5,3,0, 2, 2, 70.95, , .95, 0, 0,0,,
  546.88  626.88
   70.95   70.95
   67.45   67.45
  548.58  628.58
   70.95   70.95
   67.45   67.45
BR Coef=-1 , 0 , 0 ,, 0 ,,,.8,0,,0,
WSPro=,,,, 1 ,,,, 0 ,,,, 0 ,,,,-1 ,-1 ,-1 , 0 , 0 , 0 , 0 , 0
BC Design=,, 0 ,, 0 ,,,,,,
BC HTab HWMax=76.07

Type RM Length L Ch R = 1 ,8352.148,64.35,140.88,297.15
BEGIN DESCRIPTION:
d/s of 42" steel pipeline # 2
END DESCRIPTION:
XS GIS Cut Line= 4
      3055856.05    13845581.845     3055350.758    13845753.366
      3055312.69    13845798.886     3054909.021    13846190.584
#Sta/Elev= 28
       0   72.57    8.57   72.89  103.79   72.94  278.74    73.2  358.27   76.12
  485.36   73.89  549.83   72.65  559.28   68.49  575.31   60.61  578.58   59.75
  580.58   57.75  587.58   57.25  594.58   57.65  596.58   58.85  599.58   59.85
  608.81   62.68  618.98   67.18  630.03    72.8  636.25   72.43  640.64   72.89
   695.1   71.87  712.69   70.65  749.11   72.21  858.52   74.81  927.32   74.73
  946.41   75.03 1017.08   72.95 1155.42   73.56
#Mann= 3 ,-1 , 0
       0     .99       0  549.83    .035       0  630.03     .99       0
Bank Sta=549.83,630.03
XS Rating Curve= 0
Exp/Cntr=.5,.3

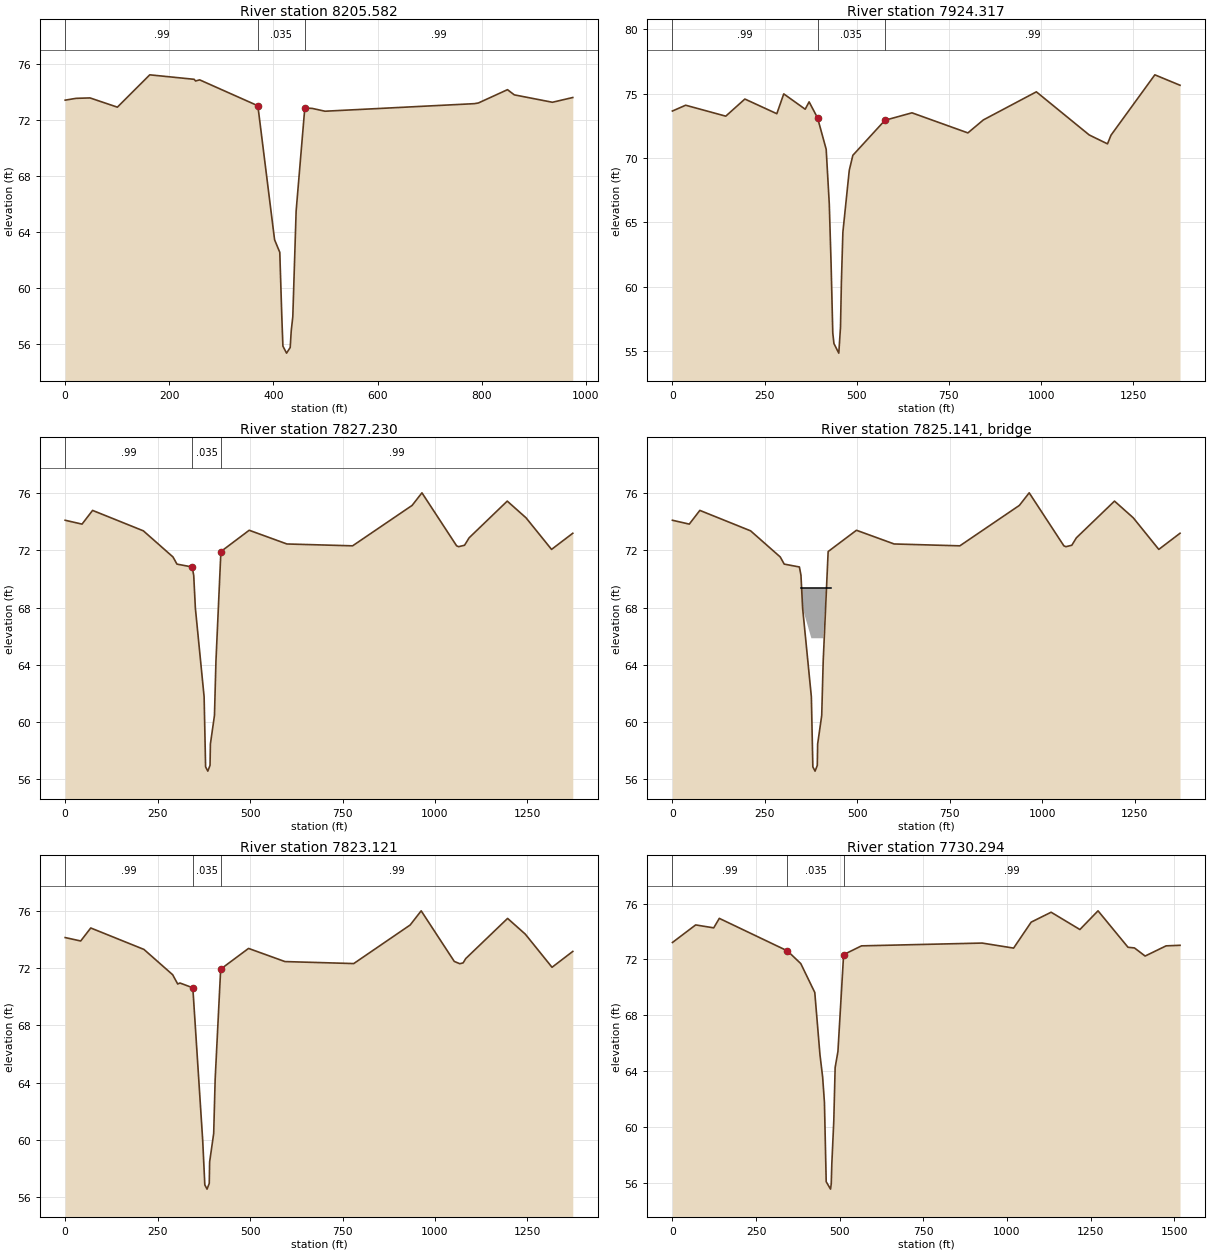
Type RM Length L Ch R = 1 ,8205.582,241,277.56,427.28
XS GIS Cut Line= 5
     3055661.439     13845633.34     3055293.501    13845676.979
     3055260.893    13845677.273     3055220.449    13845677.637
     3054693.143     13845741.45
#Sta/Elev= 27
       0   73.42   20.73   73.55   47.69   73.58  100.25   72.92  162.42   75.23
  247.69   74.91  250.38   74.79  258.27   74.87  370.01   73.02   402.1   63.45
   412.1   62.55   416.1   57.85   418.1   55.85   425.1   55.35   432.1   55.75
   434.1   56.95   437.1   57.95   443.5    65.5  460.13   72.86  474.61   72.83
  498.93   72.63  785.63   73.17  793.49   73.22  849.36   74.17  862.36    73.8
  935.65   73.27  974.72   73.61
#Mann= 3 ,-1 , 0
       0     .99       0  370.01    .035       0  460.13     .99       0
Bank Sta=370.01,460.13
XS Rating Curve= 0
Exp/Cntr=.3,.1

Type RM Length L Ch R = 1 ,7924.317,61.54,95.57,174.51
BEGIN DESCRIPTION:
G
END DESCRIPTION:
XS GIS Cut Line= 4
     3055672.073     13845618.69      3055334.66     13845416.42
     3055245.459    13845390.396     3054438.927    13845012.148
#Sta/Elev= 30
       0   73.65   35.98    74.1  144.71   73.25  196.55   74.58  283.23   73.44
  302.05   74.98  360.19   73.79  370.84   74.36  393.86   73.11  417.14   70.68
  425.56   66.44  430.49   61.75  435.06   56.42  438.23   55.59  451.37   54.85
     456   56.86  458.49   60.45  462.49   64.25   479.8   69.05  489.49   70.21
  576.55   72.93  649.86   73.51  801.58   71.95  843.65   72.96  987.36   75.14
 1130.81   71.79 1180.32    71.1  1189.8   71.77 1308.82   76.46 1377.14   75.65
#Mann= 3 ,-1 , 0
       0     .99       0  393.86    .035       0  576.55     .99       0
Bank Sta=393.86,576.55
XS Rating Curve= 0
Exp/Cntr=.5,.3

Type RM Length L Ch R = 1 ,7827.230,4.33,4.05,4.21
BEGIN DESCRIPTION:
u/s of 42" pipeline #1
END DESCRIPTION:
XS GIS Cut Line= 4
     3055628.036    13845566.044      3055375.04    13845348.042
     3055298.264    13845294.223     3054556.878    13844708.236
#Sta/Elev= 30
       0   74.11   45.63   73.84   74.16    74.8  211.39   73.37  291.62   71.54
  302.33   71.04  343.37   70.84  347.62   70.26   352.1   67.96  375.75   61.75
  379.75   56.85  385.75   56.55  391.75   56.95  392.75   58.45  403.75   60.45
  407.75   64.25  421.15   71.92  497.68   73.41  599.62   72.45  777.31   72.32
  938.28   75.15  964.81   76.03  1058.6   72.32  1064.1   72.26 1080.06   72.36
 1092.36   72.88 1195.49   75.45 1246.33   74.28  1315.3   72.07 1372.73    73.2
#Mann= 3 ,-1 , 0
       0     .99       0  343.37    .035       0  421.15     .99       0
Bank Sta=343.37,421.15
XS Rating Curve= 0
Exp/Cntr=.5,.3

Type RM Length L Ch R = 3 ,7825.141,,,
BEGIN DESCRIPTION:
42" steel pipeline # 1
END DESCRIPTION:
Bridge Culvert--1,0,-1,-1, 0
Deck Dist Width WeirC Skew NumUp NumDn MinLoCord MaxHiCord MaxSubmerge Is_Ogee
.02,3.5,3,0, 2, 2, 69.35, , .95, 0, 0,0,,
  346.75  429.75
   69.35   69.35
   65.85   65.85
  344.65  427.65
   69.35   69.35
   65.85   65.85
BR Coef=-1 , 0 , 0 ,, 0 ,,,.8,0,,0,
WSPro=,,,, 1 ,,,, 0 ,,,, 0 ,,,,-1 ,-1 ,-1 , 0 , 0 , 0 , 0 , 0
BC Design=,, 0 ,, 0 ,,,,,,
BC HTab HWMax=76.03

Type RM Length L Ch R = 1 ,7823.121,47.69,91.94,136.75
BEGIN DESCRIPTION:
d/s of 42" pipeline #1
END DESCRIPTION:
XS GIS Cut Line= 4
      3055630.42    13845562.784     3055377.424    13845344.782
     3055300.648    13845290.962     3054559.262    13844704.976
#Sta/Elev= 30
       0   74.15   42.02   73.91   69.17   74.82  213.02   73.32  290.69   71.55
  304.32    70.9  310.41   70.97  344.66   70.64  345.51   70.52  371.94   59.95
  377.65   56.85  383.65   56.55  389.65   56.95  390.65   58.45  401.65   60.45
  405.65   64.25  420.52   71.94   495.9   73.39  594.36   72.47  780.35   72.33
  933.02   75.03  962.76   76.02 1052.26   72.48 1067.14   72.32 1076.24   72.38
 1083.26   72.68 1196.43   75.49 1244.29   74.39 1316.61   72.07 1372.73   73.18
#Mann= 3 ,-1 , 0
       0     .99       0  344.66    .035       0  420.52     .99       0
Bank Sta=344.66,420.52
XS Rating Curve= 0
Exp/Cntr=.5,.3

Type RM Length L Ch R = 1 ,7730.294,308.17,291.07,285.28
XS GIS Cut Line= 4
     3055705.185     13845625.56      3055430.94    13845294.544
     3055384.149    13845211.658     3054661.989     13844530.76
#Sta/Elev= 30
       0   73.21   69.44   74.47  123.51   74.26  140.16   74.94  343.83   72.61
  383.76    71.7  425.62   69.63  441.07   65.18  449.12   63.57  454.48   61.75
  459.75   56.07  472.74   55.54  474.79   55.91  476.59   57.37  482.48   60.45
  486.48   64.25  494.82    65.4   511.8   72.34  565.25   72.97  926.01   73.17
 1020.03   72.81 1072.59   74.67  1132.2   75.38 1218.21   74.14 1272.44   75.48
 1362.01   72.87  1381.4   72.82 1413.21   72.24 1475.93   72.97 1517.59   73.01
#Mann= 3 ,-1 , 0
       0     .99       0  343.83    .035       0   511.8     .99       0
Bank Sta=343.83,511.8
XS Rating Curve= 0
Exp/Cntr=.3,.1

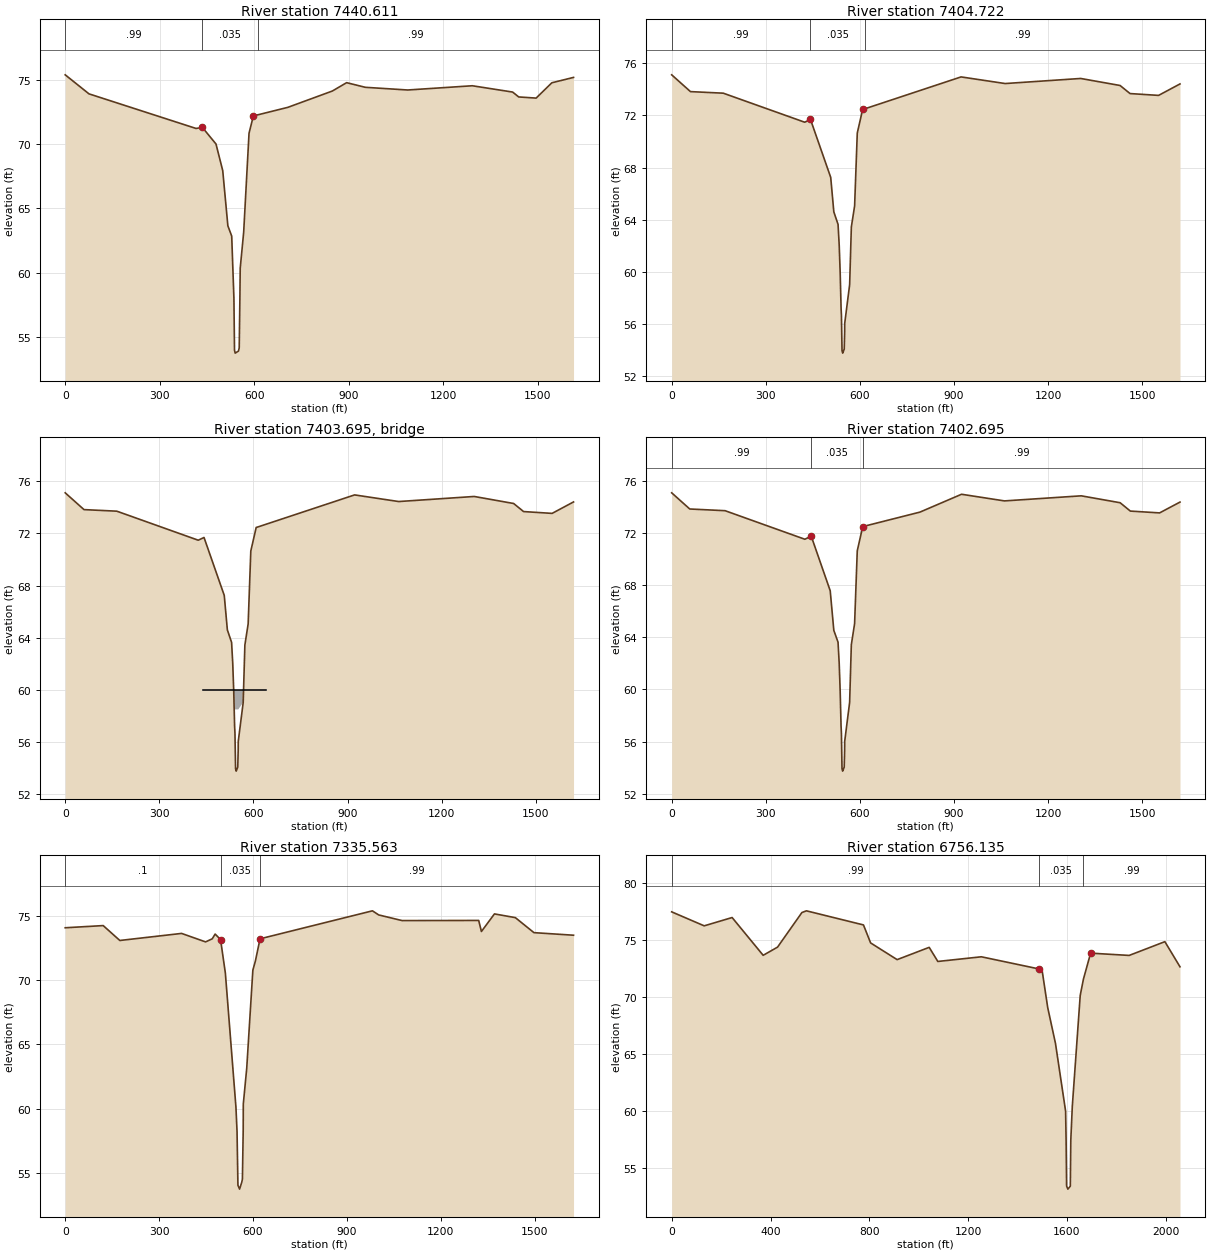
Type RM Length L Ch R = 1 ,7440.611,39.11,35.13,26.6
BEGIN DESCRIPTION:
F
END DESCRIPTION:
XS GIS Cut Line= 4
     3056049.293    13845518.493     3055685.493    13845155.954
     3055644.576     13845090.18     3054926.983    13844360.716
#Sta/Elev= 30
       0   75.39   75.55   73.91  415.46   71.22  435.66    71.3  478.88   70.01
  500.28   67.94  516.58   63.65  528.78   62.85  535.78   58.01  537.66   53.98
  539.71   53.75  550.24   53.91  552.64   54.16  554.76      58  555.78   60.35
  566.78   63.15  583.79   70.85   597.6    72.2  613.44   72.29   706.9   72.86
  848.33   74.13  893.74   74.78  952.97   74.42  1087.6   74.21 1292.84   74.54
 1420.85   74.05 1440.31   73.67 1495.51   73.58 1545.37   74.77 1614.32   75.19
#Mann= 3 ,-1 , 0
       0     .99       0  435.66    .035       0  613.44     .99       0
Bank Sta=435.66,597.6
XS Rating Curve= 0
Exp/Cntr=.5,.3

Type RM Length L Ch R = 1 ,7404.722,2.04,2,2.02
BEGIN DESCRIPTION:
u/s side of 14" steel pipeline
END DESCRIPTION:
XS GIS Cut Line= 2
     3056082.094    13845506.561     3054953.947    13844343.413
#Sta/Elev= 30
       0   75.12   59.93   73.83  164.48   73.71  424.02   71.48  442.51   71.69
  506.99   67.24   516.9   64.59  530.38   63.63  534.06   62.02  537.21   59.87
     540    57.2  541.14   56.65  543.05   53.93  545.12   53.74  550.05   54.05
  551.42   55.34   551.6   56.02  567.35   59.01  572.75   63.43  583.18   65.05
  591.65   70.65  608.79   72.46  615.74   72.51  922.51   74.96    1063   74.45
 1303.83   74.84 1429.44    74.3 1461.16   73.68 1552.12   73.54 1620.38   74.42
#Mann= 3 ,-1 , 0
       0     .99       0  442.51    .035       0  615.74     .99       0
Bank Sta=442.51,608.79
XS Rating Curve= 0
Exp/Cntr=.5,.3

Type RM Length L Ch R = 3 ,7403.695,,,
BEGIN DESCRIPTION:
14" steel pipeline
END DESCRIPTION:
Bridge Culvert--1,0,-1,-1, 0
Deck Dist Width WeirC Skew NumUp NumDn MinLoCord MaxHiCord MaxSubmerge Is_Ogee
.01,1.94,3,0, 2, 2, 59.98, , .95, 0, 0,0,,
   439.8   639.8
   59.98   59.98
   58.48   58.48
  439.69  639.69
   59.98   59.98
   58.48   58.48
BR Coef=-1 , 0 , 0 ,, 0 ,,,.8,0,,0,
WSPro=,,,, 1 ,,,, 0 ,,,, 0 ,,,,-1 ,-1 ,-1 , 0 , 0 , 0 , 0 , 0
BC Design=,, 0 ,, 0 ,,,,,,
BC HTab HWMax=75.12

Type RM Length L Ch R = 1 ,7402.695,68.87,67.39,68.17
BEGIN DESCRIPTION:
d/s side of 14" steel pipeline
END DESCRIPTION:
XS GIS Cut Line= 2
     3056083.677    13845505.377      3054955.63    13844342.333
#Sta/Elev= 30
       0   75.08   57.65   73.84  170.21   73.71  424.48   71.52  444.79   71.76
  505.34   67.57  516.85   64.53  530.27   63.63  533.95   62.02   537.1   59.87
  539.89    57.2  541.03   56.65  542.94   53.93  545.01   53.74  549.94   54.05
  551.31   55.34  551.49   56.02  567.24   59.01  572.64   63.43  583.07   65.05
  591.55   70.63  608.94   72.49  791.18    73.6  923.97   74.97 1060.63   74.46
 1305.53   74.85 1429.44   74.32 1461.96   73.68 1555.21   73.54 1620.24   74.37
#Mann= 3 ,-1 , 0
       0     .99       0  444.79    .035       0  608.94     .99       0
Bank Sta=444.79,608.94
XS Rating Curve= 0
Exp/Cntr=.5,.3

Type RM Length L Ch R = 1 ,7335.563,628.48,579.46,590.93
XS GIS Cut Line= 2
     3056142.805    13845471.423     3055012.374    13844305.921
#Sta/Elev= 30
       0   74.08  121.32   74.25  174.52   73.09  371.76   73.64   448.3   72.98
  469.68   73.22  478.93   73.59  496.26   73.16  511.57   70.55  545.36    60.1
  548.86   58.21  551.72   54.02  556.97   53.72   563.8   54.25  566.01   54.49
  568.54   58.31  568.86   60.35  579.86   63.15  599.41   70.78  607.59    71.5
  622.34   73.22  981.29    75.4 1001.35   75.08 1076.03   74.64 1320.74   74.65
 1329.47   73.79 1371.06   75.16 1437.82   74.87 1497.23    73.7 1623.66    73.5
#Mann= 3 ,-1 , 0
       0      .1       0  496.26    .035       0  622.34     .99       0
Bank Sta=496.26,622.34
XS Rating Curve= 0
Exp/Cntr=.3,.1

Type RM Length L Ch R = 1 ,6756.135,300.87,250.63,141.44
XS GIS Cut Line= 4
     3057522.664    13845587.549     3056214.146    13844718.265
      3056162.78    13844653.614     3055864.586    13844381.356
#Sta/Elev= 30
       0   77.47  131.62   76.24  244.66   76.97  370.32   73.65  428.53   74.37
  527.11   77.41  545.39   77.56  776.29   76.32  805.13   74.74  912.47   73.27
 1042.26   74.35 1077.18   73.11 1253.43   73.52 1487.08   72.45 1499.49   72.29
 1521.97   69.05 1553.33   65.91 1594.38   59.95 1596.38   57.37  1598.4   53.37
 1603.52    53.1 1613.44   53.36 1615.34   57.39 1621.38   60.35 1653.52   70.13
 1666.42   71.55 1695.55   73.84 1851.64   73.64 1996.09   74.85 2057.31   72.64
#Mann= 3 ,-1 , 0
       0     .99       0 1487.08    .035       0 1666.42     .99       0
Bank Sta=1487.08,1695.55
XS Rating Curve= 0
Exp/Cntr=.3,.1

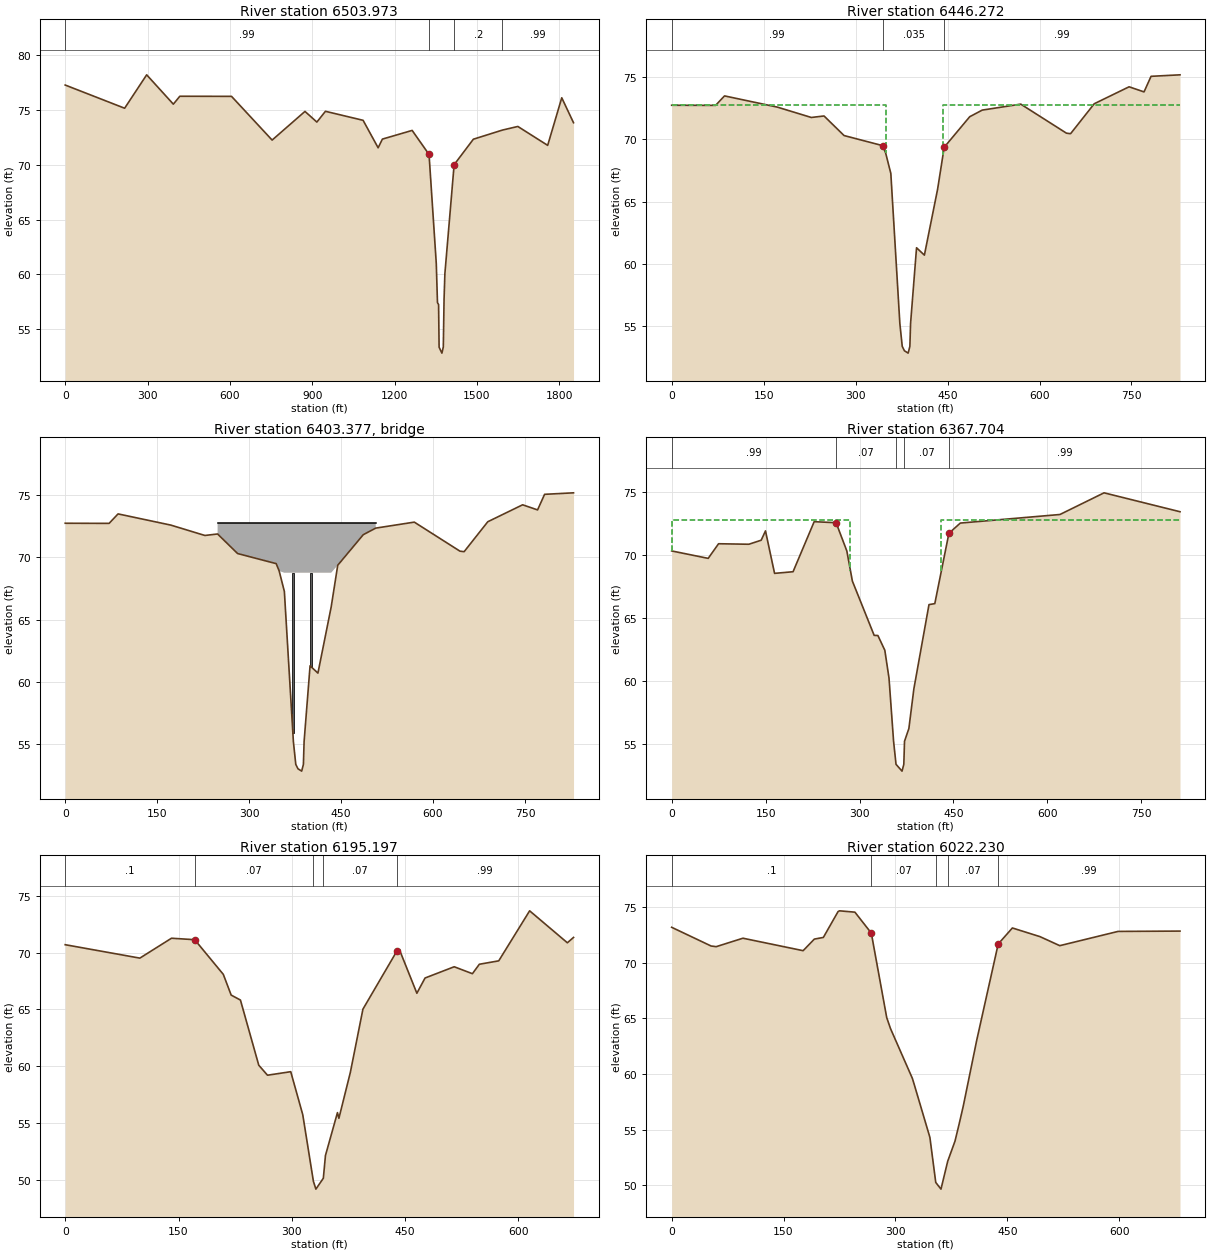
Type RM Length L Ch R = 1 ,6503.973,165.54,59.44,52.38
BEGIN DESCRIPTION:
E
END DESCRIPTION:
XS GIS Cut Line= 4
     3057587.911    13845118.632     3056290.654    13844472.909
     3056154.571    13844471.571     3055928.793    13844328.632
#Sta/Elev= 30
       0   77.24  216.56   75.13  296.87   78.17  394.07    75.5  417.66   76.22
  606.15   76.21  754.02   72.23  873.77   74.84   917.1   73.87  948.33   74.85
 1085.55   74.03 1140.34   71.53 1155.92   72.32 1264.34   73.11 1325.89   70.92
 1352.25   60.99 1356.59   57.43 1360.64   57.26 1362.53   53.38 1372.73   52.84
 1377.86    53.4 1380.59   57.75  1383.6   60.08 1417.29   69.99 1487.36   72.31
 1593.06   73.14  1649.5   73.47 1758.17   71.75 1809.48   76.08 1852.39   73.81
#Mann= 4 ,-1 , 0
       0     .99       0 1325.89    .035       0 1417.29      .2       0
 1593.06     .99       0
Bank Sta=1325.89,1417.29
XS Rating Curve= 0
Exp/Cntr=.5,.3

Type RM Length L Ch R = 1 ,6446.272,71.46,80.81,67.21
BEGIN DESCRIPTION:
u/s face of Memorial Dr. Br.
END DESCRIPTION:
XS GIS Cut Line= 3
     3056799.197    13844467.412     3056238.184    13844447.357
     3055948.168    13844309.751
#Sta/Elev= 30
       0   72.72  71.623   72.71  86.217   73.47 172.387   72.57  227.81   71.74
 248.521   71.86 281.203   70.29 344.181   69.48  349.03   68.89 357.487   67.25
 372.203   55.21 376.112   53.38 379.664   53.03 385.697   52.84 388.553   53.38
 389.672   55.21 399.426   61.29 412.234    60.7  433.79   65.99  444.54   69.35
 486.169    71.8 506.532   72.33 569.416   72.81 643.962   70.48 650.709   70.44
 689.293   72.84 746.125    74.2 770.501   73.79 781.975   75.04 829.166   75.16
#Mann= 3 ,-1 , 0
       0     .99       0 344.181    .035       0  444.54     .99       0
#XS Ineff= 2 , 0
       0  349.03   72.75 442.623       0   72.75
Permanent Ineff=
       F       F
Bank Sta=344.181,444.54
XS Rating Curve= 0
Skew Angle= 20
Exp/Cntr=.5,.3

Type RM Length L Ch R = 3 ,6403.377,,,
BEGIN DESCRIPTION:
Memorial Dr. Bridge
END DESCRIPTION:
Bridge Culvert--1,0,-1,-1, 0
Deck Dist Width WeirC Skew NumUp NumDn MinLoCord MaxHiCord MaxSubmerge Is_Ogee
.15,71.05,2.6,20, 2, 2, 72.75, , .95, 0, 0,0,,
 248.521 506.532
   72.75   72.75
   68.75   68.75
 262.588 460.976
   72.75   72.75
   68.75   68.75
Pier Skew, UpSta & Num, DnSta & Num=  ,371.32, 4 ,345.967, 4 , 3 , 3 , 0 ,,
    1.12    1.12    2.65    2.65
   51.25   66.11   66.11   68.75
    1.12    1.12    2.65    2.65
   51.25   66.11   66.11   68.75
Pier Skew, UpSta & Num, DnSta & Num=  ,401.409, 4 ,373.34, 4 , 3 , 3 , 0 ,,
    1.12    1.12    2.65    2.65
   51.25   66.11   66.11   68.75
    1.12    1.12    2.65    2.65
   51.25   66.11   66.11   68.75
BR Coef=-1 , 1 , 1 ,1.25, 0 ,,,.8,-1,2,0,
WSPro=,,,, 1 ,,,, 0 ,,,, 0 ,,,,-1 ,-1 ,-1 , 0 , 0 , 0 , 0 , 0
BC Design=,, 0 ,, 0 ,,,,,,
BC HTab HWMax=75.16

Type RM Length L Ch R = 1 ,6367.704,67.9,167.58,235.89
BEGIN DESCRIPTION:
d/s face of Memorial Dr. Br
END DESCRIPTION:
XS GIS Cut Line= 3
     3056811.038    13844398.728     3056250.026    13844378.673
     3055976.118    13844250.173
#Sta/Elev= 30
       0   70.31  58.327   69.72  74.903   70.88 123.269   70.84 142.955   71.16
 149.815    71.9 164.324   68.53 193.868   68.66 227.584   72.63 262.588   72.55
 279.728   70.31  288.58   67.92 323.395   63.61 329.334    63.6 340.413   62.43
 347.094   60.22 354.396   55.21 358.305   53.38  367.89   52.84 370.746   53.38
 371.865   55.21 378.828   56.22 386.777   59.36 410.937   66.05 420.231   66.13
 442.764   71.71 460.976   72.52 620.075    73.2 690.542   74.92 811.819   73.42
#Mann= 5 ,-1 , 0
       0     .99       0 262.588     .07       0 358.305    .035       0
 370.746     .07       0 442.764     .99       0
#XS Ineff= 2 , 0
       0 285.488   72.75 430.821       0   72.75
Permanent Ineff=
       F       F
Bank Sta=262.588,442.764
XS Rating Curve= 0
Skew Angle= 20
Exp/Cntr=.5,.3

Type RM Length L Ch R = 1 ,6195.197,108.29,175.28,234.96
XS GIS Cut Line= 2
     3056838.064    13844409.692     3056231.638    13844117.834
#Sta/Elev= 30
       0   70.69   98.84   69.51  140.74   71.26  171.44   71.13  209.34   68.08
  219.72   66.26  232.01   65.82  256.26   60.09  267.82   59.21   298.6   59.52
   314.5   55.74  328.57   49.89  331.89   49.19  341.76   50.15  344.57   52.15
  360.46   55.92  362.36   55.42  377.52   59.46  394.17   65.02  439.12   70.13
  442.87   70.19  465.58   66.42  476.41   67.76  515.01   68.75  539.14   68.14
   548.3   68.97  573.98   69.27  614.89   73.67  664.83   70.86     673   71.33
#Mann= 5 ,-1 , 0
       0      .1       0  171.44     .07       0  328.57    .035       0
  341.76     .07       0  439.12     .99       0
Bank Sta=171.44,439.12
XS Rating Curve= 0
Exp/Cntr=.3,.1

Type RM Length L Ch R = 1 ,6022.230,52.37,55.07,44.29
BEGIN DESCRIPTION:
D
END DESCRIPTION:
XS GIS Cut Line= 4
     3056930.891     13844408.03     3056675.396    13844174.773
     3056644.874    13844119.567     3056449.268     13843929.95
#Sta/Elev= 30
       0   73.17   52.85   71.49   59.68   71.43   95.53   72.19  176.25   71.07
  191.25   72.11  203.35   72.26  223.06   74.58  225.06   74.65  245.66   74.53
  267.05    72.7  267.56   72.68  288.29   65.06  293.32   64.08  322.68    59.6
  324.65   59.17  346.18    54.3  354.04   50.25  361.04   49.65  370.04   52.15
  379.83   53.96  385.35   55.49  390.83   57.08  409.04   63.05  437.75   71.67
  456.76   73.11  493.81   72.33  520.29   71.52  598.39    72.8  681.47   72.83
#Mann= 5 ,-1 , 0
       0      .1       0  267.05     .07       0  354.04    .035       0
  370.04     .07       0  437.75     .99       0
Bank Sta=267.05,437.75
XS Rating Curve= 0
Exp/Cntr=.5,.3

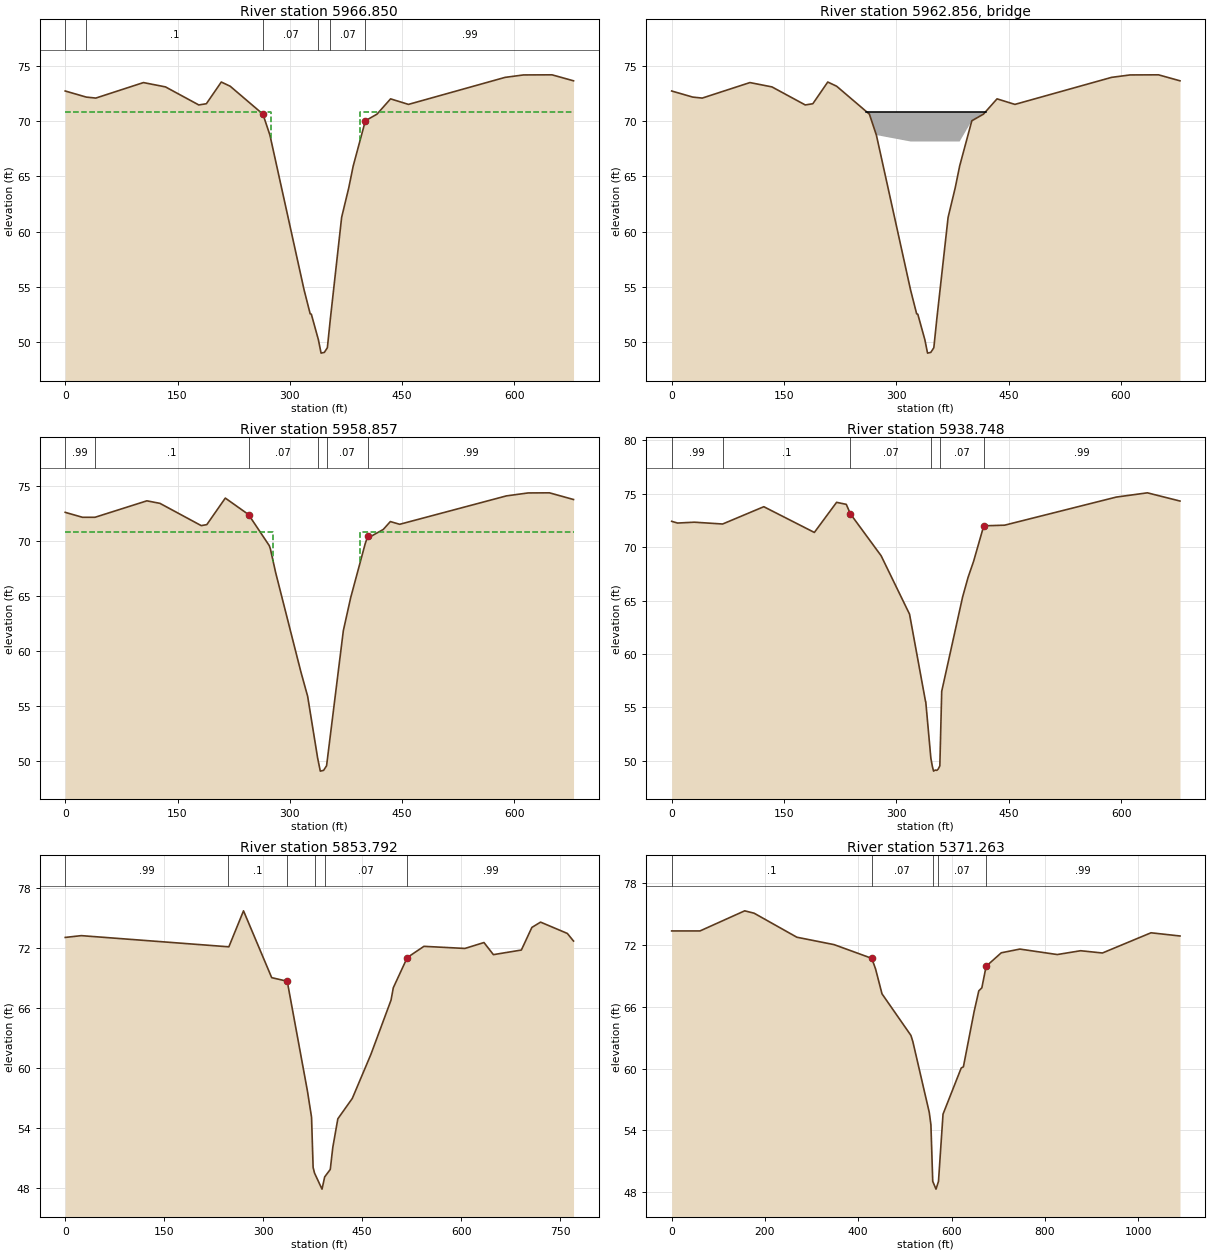
Type RM Length L Ch R = 1 ,5966.850,7.97,8,7.95
BEGIN DESCRIPTION:
u/s side of Nature Reserve Footbridge, from Klotz
END DESCRIPTION:
XS GIS Cut Line= 4
      3056951.17    13844367.082     3056728.134    13844145.152
     3056689.091    13844099.486     3056469.547    13843889.002
#Sta/Elev= 30
       0   72.71    28.1   72.16   40.83   72.07   104.5   73.47  133.91   73.08
  178.41   71.45  188.52   71.56  208.46   73.52  220.34   73.14  264.03   70.62
  273.38   68.73  319.03   54.75  327.15   52.59  328.69   52.56  338.13   50.25
  341.72   49.04  346.12   49.11  350.11   49.53  354.13   52.15  369.17    61.3
  378.65   63.96  384.62   65.94  400.85   70.02   416.4   70.62  434.52      72
  458.41    71.5  587.45   73.94   612.1   74.16  650.15   74.17  678.86   73.63
#Mann= 6 ,-1 , 0
       0     .99       0    28.1      .1       0  264.03     .07       0
  338.13    .035       0  354.13     .07       0  400.85     .99       0
#XS Ineff= 2 , 0
       0  275.27   70.85  393.41       0   70.85
Permanent Ineff=
       F       F
Bank Sta=264.03,400.85
XS Rating Curve= 0
Exp/Cntr=.5,.3

Type RM Length L Ch R = 3 ,5962.856,,,
BEGIN DESCRIPTION:
Nature Reserve Footbridge
END DESCRIPTION:
Bridge Culvert--1,0,-1,-1, 0
Deck Dist Width WeirC Skew NumUp NumDn MinLoCord MaxHiCord MaxSubmerge Is_Ogee
.01,7.98,2.6,0, 2, 2, 70.85, , .95, 0, 0,0,,
     260     420
   70.85   70.85
   68.15   68.15
     260     420
   70.85   70.85
   68.15   68.15
BR Coef=-1 , 0 , 0 ,, 0 ,,,.8,-1,,0,
WSPro=,,,, 1 ,,,, 0 ,,,, 0 ,,,,-1 ,-1 ,-1 , 0 , 0 , 0 , 0 , 0
BC Design=,, 0 ,, 0 ,,,,,,
BC HTab HWMax=74.17

Type RM Length L Ch R = 1 ,5958.857,22.8,20.5,20.6
BEGIN DESCRIPTION:
d/s side of Nature Reserve Footbridge, from Klotz
END DESCRIPTION:
XS GIS Cut Line= 4
     3056957.224    13844361.869     3056734.188    13844139.939
     3056695.145    13844094.273     3056475.601    13843883.789
#Sta/Elev= 30
       0   72.64      23   72.19   39.81   72.19  109.07   73.69  126.51   73.46
  181.66   71.43  189.12   71.52  213.82   73.94  244.81   72.44  272.57    69.6
  273.97   69.32  281.07   67.14  314.64   58.12  323.76   55.87  337.08   50.25
  340.67   49.04  345.07   49.11  349.06   49.53  371.44   61.85  381.24   64.86
  400.56   69.76     404   70.46  408.83   70.47  424.78   71.08  434.23    71.8
  446.68   71.55  589.18   74.14  618.29   74.41  646.72   74.42  678.86   73.81
#Mann= 6 ,-1 , 0
       0     .99       0   39.81      .1       0  244.81     .07       0
  337.08    .035       0  349.06     .07       0     404     .99       0
#XS Ineff= 2 , 0
       0  277.78   70.85  394.21       0   70.85
Permanent Ineff=
       F       F
Bank Sta=244.81,404
XS Rating Curve= 0
Exp/Cntr=.5,.3

Type RM Length L Ch R = 1 ,5938.748,92.98,83.66,91.59
XS GIS Cut Line= 2
     3056974.462    13844346.604     3056492.839    13843868.524
#Sta/Elev= 29
       0   72.43    7.96   72.27   30.29   72.35   68.04   72.18  122.99    73.8
  190.48   71.39  220.17   74.21  233.13   74.02   238.5   73.14  279.61   69.21
  317.55   63.74  338.94   55.55  339.21   55.54  346.03   50.25  348.03   49.48
  349.62   49.04  351.77   49.14  354.02   49.11  355.79   49.23  358.01   49.53
   360.5   56.51  388.38   65.34  395.72   67.19  403.09   68.69  416.63   72.01
  444.48   72.07  593.41    74.7  635.07    75.1  678.62   74.33
#Mann= 6 ,-1 , 0
       0     .99       0   68.04      .1       0   238.5     .07       0
  346.03    .035       0  358.01     .07       0  416.63     .99       0
Bank Sta=238.5,416.63
XS Rating Curve= 0
Exp/Cntr=.3,.1

Type RM Length L Ch R = 1 ,5853.792,512.06,487.81,366.05
XS GIS Cut Line= 4
     3057115.582    13844295.375     3056815.376      13844084.1
     3056781.171    13844025.304     3056542.834    13843789.521
#Sta/Elev= 30
       0   73.04   24.36   73.22   246.4   72.11  248.02    72.1  270.24    75.7
  312.94   69.02   336.5   68.66   367.1   57.69  373.33   55.07  375.72   50.05
  377.82   49.49  389.19   47.88  393.24    49.1  401.72   49.85  405.54   52.05
  413.18   54.91  435.12   56.95  463.29   61.35  493.83   66.78  497.23   68.01
  518.41   71.03  543.66   72.15  605.79   71.94  634.65   72.53  648.96   71.32
  691.32   71.78  707.24   74.04  720.44   74.57  760.97   73.44  770.38   72.68
#Mann= 6 ,-1 , 0
       0     .99       0   246.4      .1       0   336.5     .07       0
  377.82    .035       0  393.24     .07       0  518.41     .99       0
Bank Sta=336.5,518.41
XS Rating Curve= 0
Exp/Cntr=.3,.1

Type RM Length L Ch R = 1 ,5371.263,69,81.46,84.5
XS GIS Cut Line= 2
     3057476.483    13843851.202     3056470.231     13843432.39
#Sta/Elev= 30
       0   73.35   60.79   73.35  156.56    75.3  176.76   75.07  268.42   72.74
  348.36   72.02   429.1   70.69  437.19   69.66  450.99   67.25  512.96   63.22
  517.11   62.62  552.32   55.75  555.86   54.55  559.76   49.07  566.77   48.31
   572.1   49.06  581.82   55.58  620.86   60.06   625.5   60.17  648.53   65.54
  658.55   67.54  665.05   67.83  674.24   69.92  706.74   71.23  746.55   71.59
  826.79   71.06  876.85   71.43  923.59   71.21 1027.75   73.17 1089.93   72.86
#Mann= 5 ,-1 , 0
       0      .1       0   429.1     .07       0  559.76    .035       0
   572.1     .07       0  674.24     .99       0
Bank Sta=429.1,674.24
XS Rating Curve= 0
Exp/Cntr=.3,.1