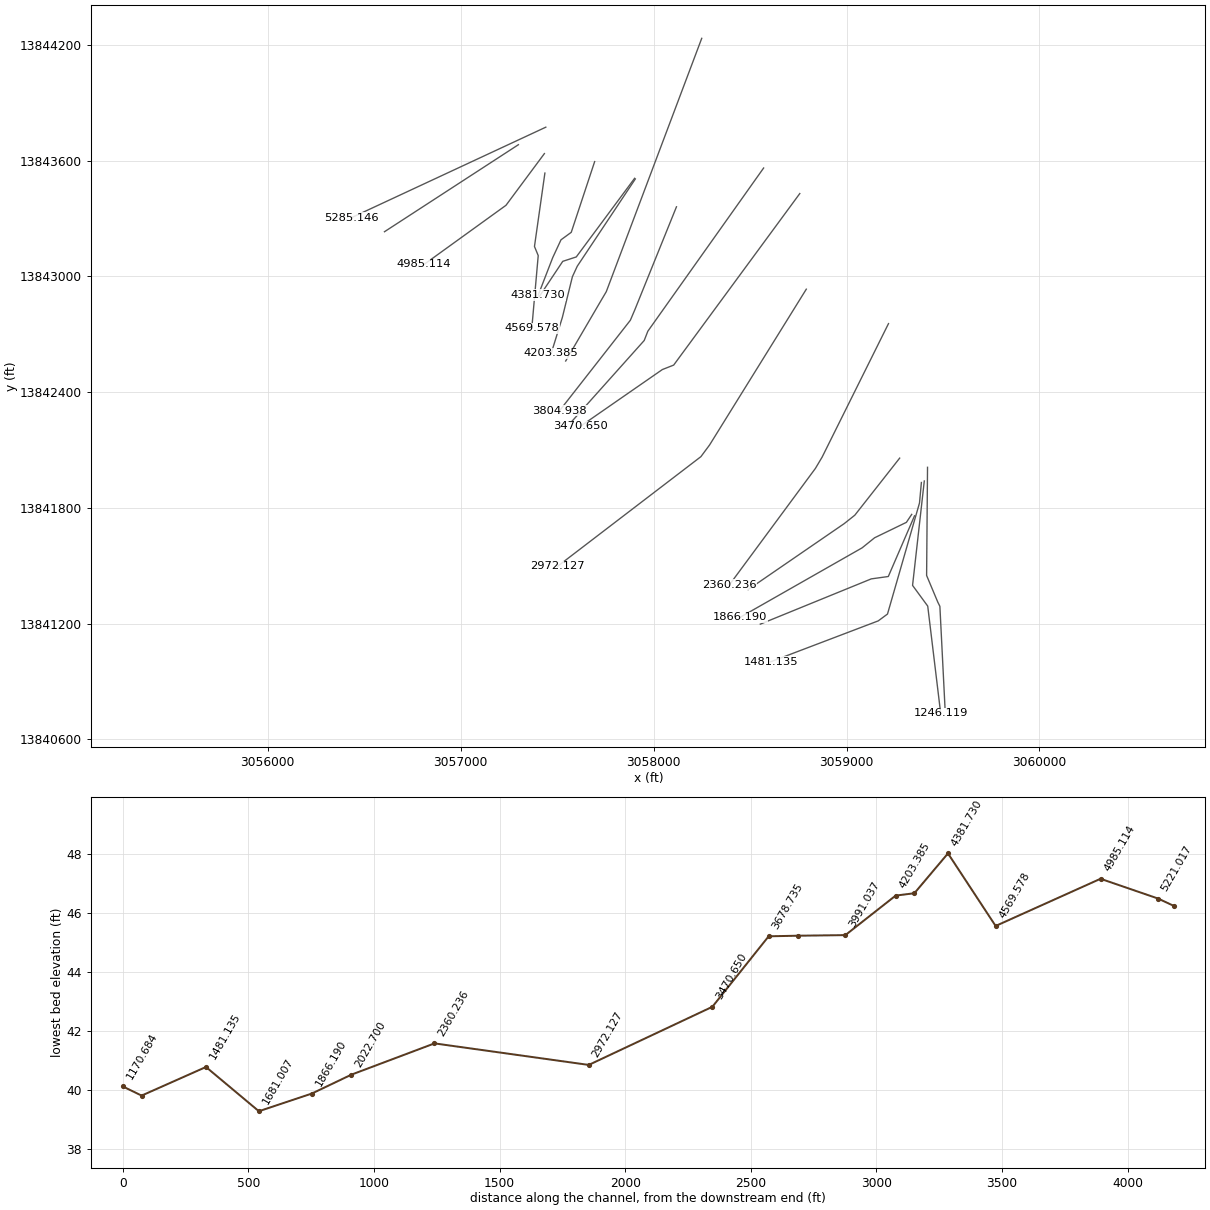
HEC-RAS study W156-00-00.prj: W156-00-00

--- W156-00-00.g02 (geometry) --- (continued)

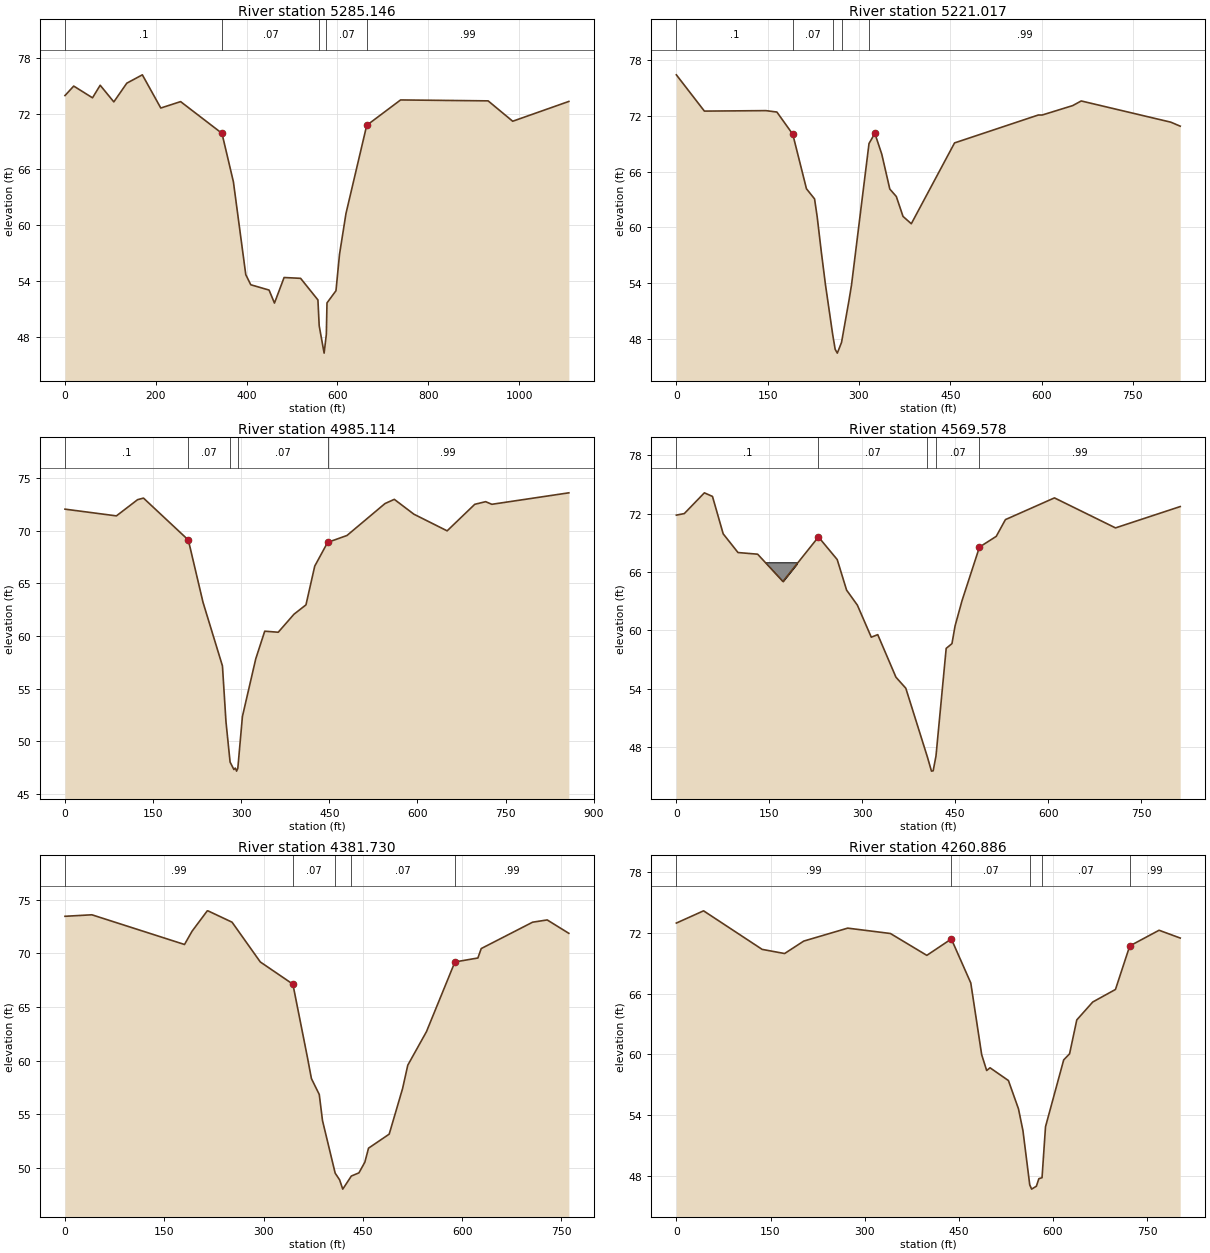
Type RM Length L Ch R = 1 ,5285.146,33.97,62.96,83.92
XS GIS Cut Line= 2
     3057441.449    13843773.193     3056435.483    13843304.752
#Sta/Elev= 30
       0   73.93   19.24   74.95   60.63   73.69   77.52   75.04  107.57   73.25
  136.11   75.26   170.4   76.16  210.99   72.59  254.64   73.28  345.72   69.87
  370.91   64.66  398.16   54.68  409.18   53.59  449.45   53.02  461.37   51.62
  482.55   54.37  518.94   54.28  557.06   51.96  559.87   49.18  570.72   46.24
  575.59   48.25  577.04   51.64  596.84   52.95  604.61   56.86  618.84   61.25
  664.55   70.73  739.11   73.46  931.93   73.36  986.01   71.17 1109.69    73.3
#Mann= 5 ,-1 , 0
       0      .1       0  345.72     .07       0  559.87    .035       0
  575.59     .07       0  664.55     .99       0
Bank Sta=345.72,664.55
XS Rating Curve= 0
Exp/Cntr=.3,.1

Type RM Length L Ch R = 1 ,5221.017,176.54,229.02,239.5
XS GIS Cut Line= 2
     3057299.392    13843682.358     3056605.297    13843231.362
#Sta/Elev= 30
       0   76.41   46.04   72.51  147.17   72.56  165.16   72.41  191.27   70.02
  213.74   64.16  227.05   63.07   231.4   61.13   238.1    57.4  244.93   53.86
  256.76   48.52  260.91    46.9  264.41   46.49  271.32   47.63  283.76   52.22
  287.74   53.81  316.49   69.02  326.08   70.12  337.46   67.88  350.67   64.13
  361.35   63.33  372.36   61.19  385.98    60.4  457.02   69.09  594.61   72.09
  601.06   72.09  651.06    73.1  665.12    73.6  812.28   71.32  827.75   70.89
#Mann= 5 ,-1 , 0
       0      .1       0  191.27     .07       0  256.76    .035       0
  271.32     .07       0  316.49     .99       0
#Block Obstruct= 2 , 0
       0                  337.46       0      67
Bank Sta=191.27,326.08
XS Rating Curve= 0
Exp/Cntr=.3,.1

Type RM Length L Ch R = 1 ,4985.114,147.41,417.68,457.86
XS GIS Cut Line= 3
     3057434.115    13843636.302     3057235.016    13843368.262
     3056810.196    13843061.561
#Sta/Elev= 30
       0   72.04   87.57    71.4  123.62   72.94  133.64   73.09     210   69.11
  235.02   63.19   268.1   57.15   274.1   51.85   281.1   48.02   287.6   47.31
  289.97   47.45  292.18   47.16  294.26   47.43   302.1   52.35  324.83   57.83
  340.09   60.45  363.08   60.35  389.86   62.06  410.28   62.95  425.23   66.63
  447.13   68.88  480.15   69.54  544.81   72.57  560.69   72.97  594.05   71.56
  650.65   69.98   697.7    72.5  716.19   72.75  726.76    72.5  857.86   73.59
#Mann= 5 ,-1 , 0
       0      .1       0     210     .07       0   281.1    .035       0
  294.26     .07       0  447.13     .99       0
Bank Sta=210,447.13
XS Rating Curve= 0
Exp/Cntr=.3,.1

Type RM Length L Ch R = 1 ,4569.578,215.71,189.74,43.55
XS GIS Cut Line= 4
     3057436.693    13843535.348     3057382.664    13843154.847
     3057402.101    13843107.649     3057368.841     13842731.39
#Sta/Elev= 30
       0   71.84   12.84      72   45.22   74.13   58.29   73.76   75.59   69.92
   99.49      68  131.18   67.83  171.95   65.03   229.3    69.6  259.57   67.28
  274.73   64.14  292.13    62.6  314.56   59.31     325   59.57  354.39    55.2
  370.27   54.07  405.26   46.98  411.68   45.56  414.39   45.59  418.97   47.11
  435.42   58.16  444.75   58.65  449.78   60.47  460.99   63.06  489.13   68.56
  516.19   69.66  531.02   71.38  610.14   73.61  708.65   70.53  813.09   72.72
#Mann= 5 ,-1 , 0
       0      .1       0   229.3     .07       0  405.26    .035       0
  418.97     .07       0  489.13     .99       0
#Block Obstruct= 2 , 0
       0  194.62      67               0
Bank Sta=229.3,489.13
XS Rating Curve= 0
Exp/Cntr=.3,.1

Type RM Length L Ch R = 1 ,4381.730,157.64,133.76,23.33
BEGIN DESCRIPTION:
C
END DESCRIPTION:
XS GIS Cut Line= 5
     3057694.623    13843594.761     3057573.319     13843228.28
     3057520.137    13843189.367     3057477.333    13843097.272
     3057402.411    13842903.619
#Sta/Elev= 30
       0   73.47   40.63   73.61  180.55   70.84  191.87   72.07  214.96   73.98
  216.63   73.96  252.39   72.92  295.05   69.21  344.26   67.14  366.07   60.36
  372.28   58.33   384.1   56.85  388.99   54.42  408.15   49.51  414.82   48.89
  419.61   48.02  432.56   49.24  444.08   49.54  453.01   50.54  458.52   51.84
  489.76   53.15  509.96    57.4  517.82   59.58  546.05   62.71  589.03   69.21
  623.73   69.58  628.78   70.46  706.39   72.92  728.45   73.13  761.13   71.88
#Mann= 5 ,-1 , 0
       0     .99       0  344.26     .07       0  408.15    .035       0
  432.56     .07       0  589.03     .99       0
Bank Sta=344.26,589.03
XS Rating Curve= 0
Exp/Cntr=.3,.1

Type RM Length L Ch R = 1 ,4260.886,17.52,74.51,135.78
XS GIS Cut Line= 4
     3057901.762    13843508.205     3057599.377    13843100.693
     3057529.217    13843077.816     3057406.412    13842893.617
#Sta/Elev= 30
       0   72.96   43.35   74.17  136.69   70.36  172.44   69.95  202.93   71.18
  272.94   72.46  340.98   71.93  398.99   69.77  438.05   71.39  469.03   67.04
  486.35   59.96  494.31   58.39  499.68   58.66  528.97    57.4     545    54.6
   552.1   52.45  562.95   47.09  565.94   46.67  573.51   46.96  577.45    47.7
  582.51    47.8  588.06   52.84  617.02   59.44  626.37   60.04  637.86   63.39
  663.28   65.16  699.49    66.4  722.23    70.7  768.95   72.25  802.63   71.48
#Mann= 5 ,-1 , 0
       0     .99       0  438.05     .07       0  562.95    .035       0
  582.51     .07       0  722.23     .99       0
Bank Sta=438.05,722.23
XS Rating Curve= 0
Exp/Cntr=.3,.1

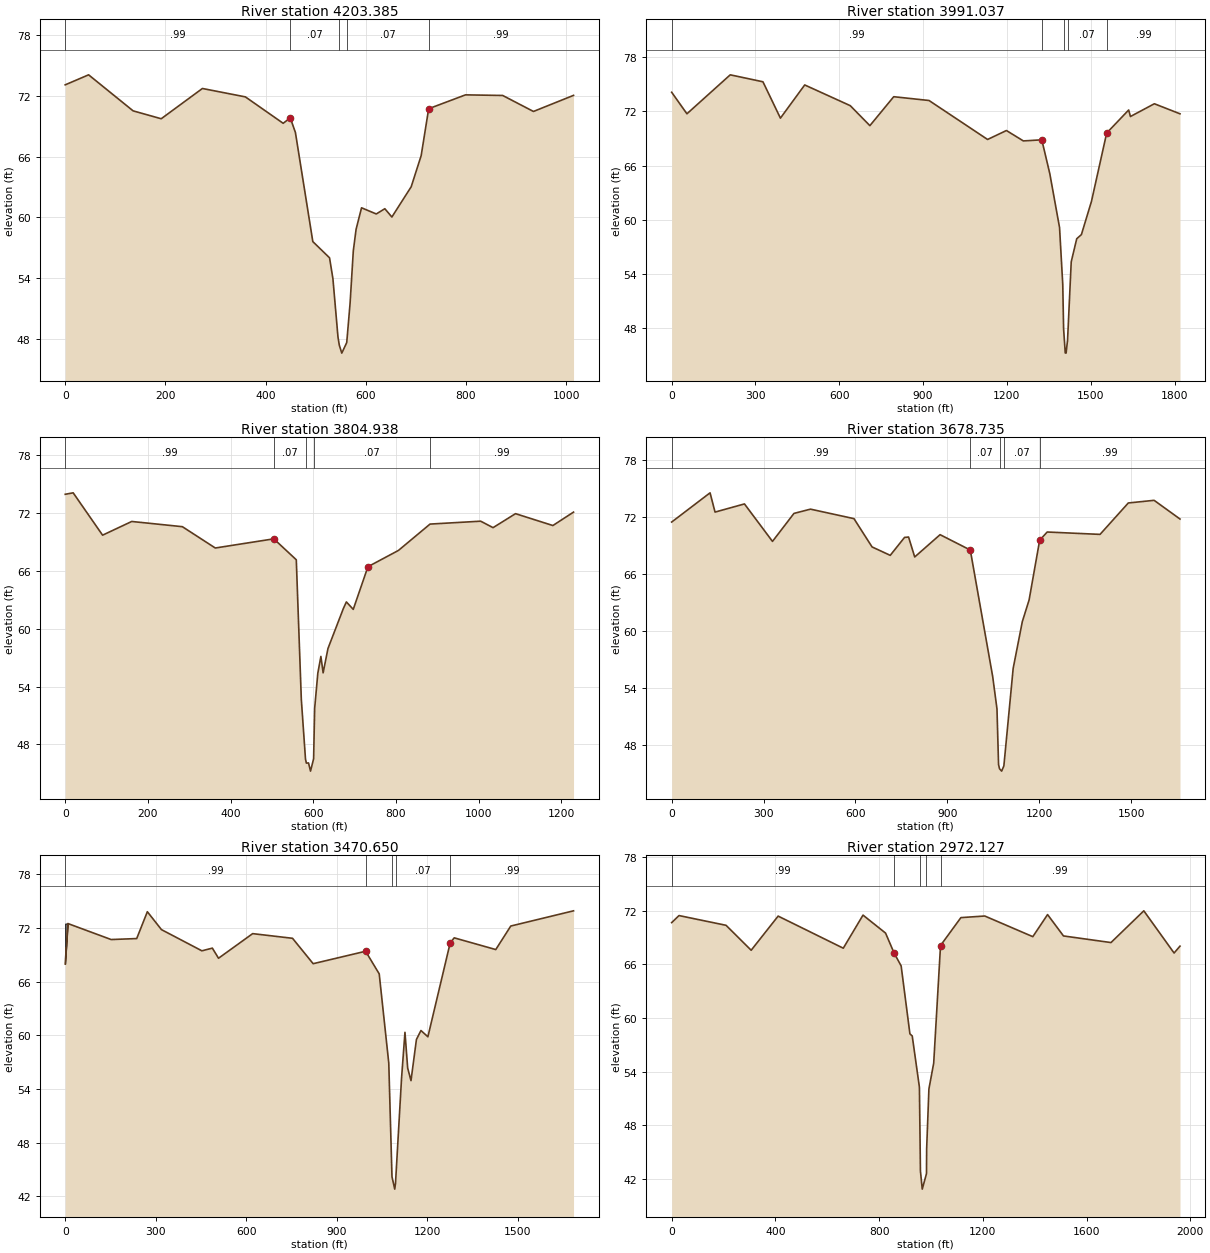
Type RM Length L Ch R = 1 ,4203.385,126.91,200.19,160.74
XS GIS Cut Line= 5
     3057905.281    13843504.689     3057604.321    13843052.383
     3057579.228    13842998.014     3057527.213    13842787.247
     3057469.496    13842601.352
#Sta/Elev= 30
       0    73.1   46.72   74.09  135.55   70.53   191.7   69.75  273.94   72.74
  359.74   71.91  435.21    69.3  449.36   69.84  459.64   68.39  494.38   57.61
  527.75   56.01  534.47   53.96   544.6   48.19  547.23   47.38  552.19   46.59
  562.07   47.63  568.76   51.51  575.23    56.7  580.74   58.82  591.65   60.95
  621.08   60.34  638.16   60.86  652.21   60.04  690.79   63.03  710.72   66.11
  725.68   70.74   799.2   72.11  873.46   72.05  934.91   70.47  1014.9   72.06
#Mann= 5 ,-1 , 0
       0     .99       0  449.36     .07       0  547.23    .035       0
  562.07     .07       0  725.68     .99       0
Bank Sta=449.36,725.68
XS Rating Curve= 0
Exp/Cntr=.3,.1

Type RM Length L Ch R = 1 ,3991.037,199.29,189.28,165.35
XS GIS Cut Line= 4
      3058249.56    13844233.656     3057754.881    13842920.643
     3057727.696    13842874.639     3057544.498    13842561.336
#Sta/Elev= 30
       0    74.1    54.6   71.72  209.65   76.03  326.71   75.26  389.27   71.24
  476.18   74.91  639.21   72.62  709.48   70.41  794.84   73.61  921.21   73.19
 1130.81   68.88 1198.18   69.87 1258.76   68.72  1324.8   68.84 1353.47    65.1
 1388.34   59.14 1399.84   52.85 1402.84   47.95 1408.78   45.27 1411.75   45.25
 1416.97   46.67 1430.16   55.35 1449.83    57.9 1466.55   58.36 1502.66   62.04
 1557.05   69.59 1635.78   72.14 1642.08   71.42 1727.74   72.83 1819.48   71.72
#Mann= 5 ,-1 , 0
       0     .99       0  1324.8     .07       0 1402.84    .035       0
 1416.97     .07       0 1557.05     .99       0
Bank Sta=1324.8,1557.05
XS Rating Curve= 0
Exp/Cntr=.3,.1

Type RM Length L Ch R = 1 ,3804.938,189.51,116.15,111.09
XS GIS Cut Line= 4
     3058118.609    13843360.494     3057903.071    13842827.419
     3057879.635    13842772.502     3057513.235    13842304.415
#Sta/Elev= 30
       0   73.93   19.27   74.08   90.38   69.69  160.86   71.11  283.29   70.57
  362.89   68.36  504.38   69.31  558.76   67.14  570.93   52.68  581.02   46.48
  583.17   46.06  588.32   46.08  593.18   45.23  600.68   46.52  603.19   51.73
  610.83   55.38  618.26   57.12  623.67   55.42  635.37   57.94  672.64   62.09
  679.88   62.77  696.52      62  732.02   66.42  805.85   68.11  882.18   70.84
 1004.62   71.14 1034.57   70.47  1088.9   71.92 1179.22   70.69 1229.15   72.08
#Mann= 5 ,-1 , 0
       0     .99       0  504.38     .07       0  583.17    .035       0
  600.68     .07       0  882.18     .99       0
Bank Sta=504.38,732.02
XS Rating Curve= 0
Exp/Cntr=.3,.1

Type RM Length L Ch R = 1 ,3678.735,224.85,224.22,132.16
XS GIS Cut Line= 4
     3058570.324    13843561.518     3057970.264    13842715.715
     3057951.445     13842667.62     3057571.149    13842242.383
#Sta/Elev= 30
       0   71.46   125.3   74.54  141.57   72.51  237.58   73.37  329.05   69.42
  399.14   72.37  452.99   72.82  594.97   71.82  654.01   68.84  713.39   67.95
  760.07   69.84  773.23   69.88  793.25   67.78  876.11   70.13  974.71   68.51
 1047.85   55.17  1061.8   51.76 1066.95    45.9  1070.1   45.46 1077.08   45.21
 1084.29   45.76 1114.65   56.04 1144.56   60.97 1166.67   63.25 1201.12   69.54
 1225.72   70.41 1398.22   70.16 1490.42   73.47 1574.64   73.75 1659.17   71.78
#Mann= 5 ,-1 , 0
       0     .99       0  974.71     .07       0  1070.1    .035       0
 1084.29     .07       0 1201.12     .99       0
Bank Sta=974.71,1201.12
XS Rating Curve= 0
Exp/Cntr=.3,.1

Type RM Length L Ch R = 1 ,3470.650,369.82,492.03,496.73
BEGIN DESCRIPTION:
Beltway 8 area blocked
END DESCRIPTION:
XS GIS Cut Line= 4
     3058757.785    13843429.181     3058104.095    13842540.062
     3058045.544     13842517.06     3057619.967    13842222.207
#Sta/Elev= 30
       0   67.99     8.8   72.51  152.22   70.72  236.93   70.83  272.18   73.83
  318.88   71.83   452.9   69.46  487.54   69.76  507.99   68.63  621.08   71.38
  753.16   70.86  821.56   68.02  995.31   69.41 1040.39   66.88  1072.1    56.9
 1082.69   44.21 1091.85   42.82 1094.34   43.45 1114.38   55.21 1125.69   60.35
 1134.69   56.35 1145.69   54.95 1163.69   59.55 1178.69   60.55 1201.69   59.85
 1275.44   70.33 1288.87   70.91 1426.55    69.6 1476.31   72.23 1684.21   73.93
#Mann= 5 ,-1 , 0
       0     .99       0  995.31     .07       0 1082.69    .035       0
 1094.34     .07       0 1275.44     .99       0
#Block Obstruct= 2 , 0
       0     8.8   72.51               0
Bank Sta=995.31,1275.44
XS Rating Curve= 0
Exp/Cntr=.3,.1

Type RM Length L Ch R = 1 ,2972.127,515.87,614.27,574.29
BEGIN DESCRIPTION:
B
END DESCRIPTION:
XS GIS Cut Line= 4
     3058791.512    13842933.529     3058290.204    13842126.023
     3058245.312    13842065.543      3057503.34    13841497.864
#Sta/Elev= 30
       0   70.66   28.25   71.45  209.74   70.36   306.5   67.57  410.52   71.39
  661.72    67.8  737.79    71.5  824.72   69.49  857.93   67.24  884.81   65.82
  918.62   58.22  927.59   57.98  954.86   52.33  955.29   52.19  959.15   42.89
  966.17   40.85   982.5   42.58  983.15   45.35  991.87   52.05 1010.37   54.95
 1036.69    68.1 1115.21   71.22 1207.28    71.4 1392.52   69.09 1449.36   71.56
 1510.76   69.17 1693.91   68.43 1820.49   71.98 1937.22   67.26 1960.01   68.03
#Mann= 5 ,-1 , 0
       0     .99       0  857.93     .07       0  959.15    .035       0
   982.5     .07       0 1036.69     .99       0
Bank Sta=857.93,1036.69
XS Rating Curve= 0
Exp/Cntr=.3,.1

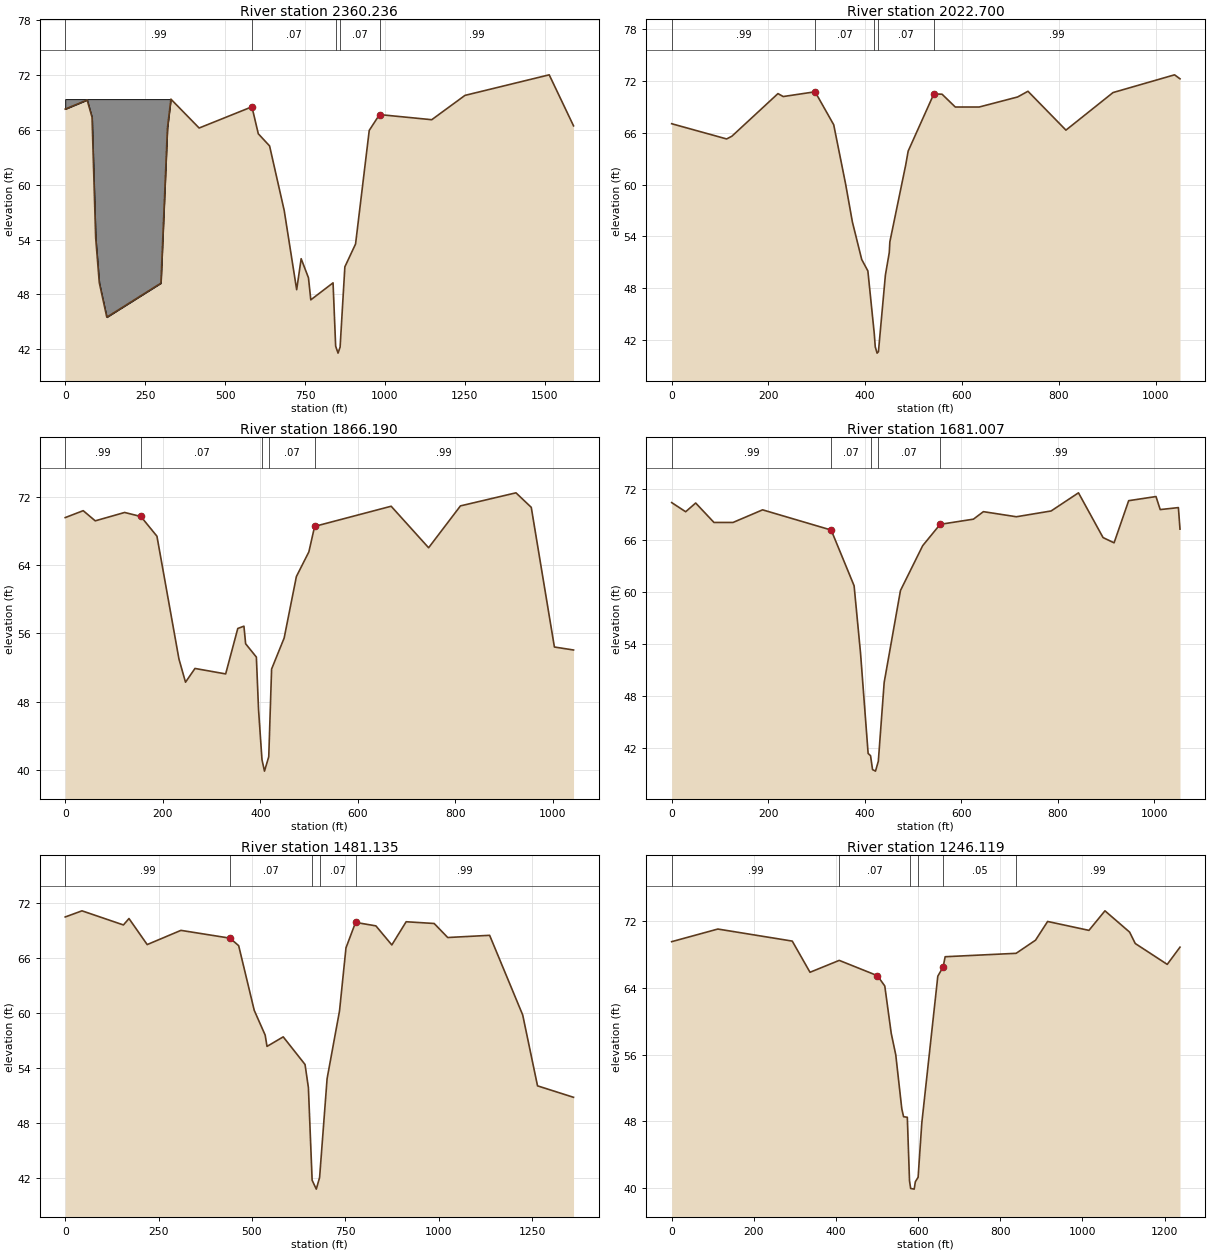
Type RM Length L Ch R = 1 ,2360.236,370.38,330.55,237.58
BEGIN DESCRIPTION:
Beltway 8 area blocked
END DESCRIPTION:
XS GIS Cut Line= 4
     3059217.564    13842755.121     3058873.622     13842063.29
     3058838.698    13842004.545     3058393.867    13841402.325
#Sta/Elev= 30
       0   68.28   68.72   69.28   83.94   67.38   95.28   54.21  106.61   49.29
  130.12   45.51  299.36   49.24  319.73    66.2  330.54   69.37  418.85   66.21
   583.9   68.53  603.87   65.58  639.14   64.25  684.86   57.19  723.84   48.52
   737.9   51.91  760.76   49.82  768.04   47.41   837.6   49.27  845.74   42.35
  853.21   41.58  859.68   42.24  874.56   51.02  908.01   53.52  950.78   65.95
  982.96   67.68 1146.26   67.12 1250.17   69.78 1513.62   72.03 1589.65   66.45
#Mann= 5 ,-1 , 0
       0     .99       0   583.9     .07       0  845.74    .035       0
  859.68     .07       0  982.96     .99       0
#Block Obstruct= 2 , 0
       0  330.54   69.37               0
Bank Sta=583.9,982.96
XS Rating Curve= 0
Exp/Cntr=.3,.1

Type RM Length L Ch R = 1 ,2022.700,236.5,157.54,137.69
XS GIS Cut Line= 4
     3059275.507    13842058.003     3059043.002    13841762.171
     3058988.205    13841718.563     3058490.095    13841376.491
#Sta/Elev= 30
       0   67.03  113.59   65.27  124.57   65.59  219.68   70.51  230.51   70.17
  296.41   70.72  334.89   66.91  359.41   60.08  373.47   55.68  392.77   51.34
  405.48   50.02  418.74   42.75  420.74   41.25  424.49   40.52   427.3   40.68
  441.74   49.55  449.74   52.15  450.92   53.38  483.67   62.26  488.78   63.87
   541.9   70.48  558.81   70.44  586.16   68.96  635.49   68.96  714.94   70.12
  736.35   70.78  814.85   66.29  912.15   70.63 1039.27   72.68 1050.55   72.22
#Mann= 5 ,-1 , 0
       0     .99       0  296.41     .07       0  418.74    .035       0
   427.3     .07       0   541.9     .99       0
Bank Sta=296.41,541.9
XS Rating Curve= 0
Exp/Cntr=.3,.1

Type RM Length L Ch R = 1 ,1866.190,97.42,210.95,135.96
BEGIN DESCRIPTION:
adjusted for skewness
END DESCRIPTION:
XS GIS Cut Line= 5
     3059337.847    13841766.353     3059310.366    13841725.045
     3059145.466    13841645.069     3059080.641    13841592.791
     3058449.764    13841233.504
#Sta/Elev= 30
       0   69.56   36.91   70.37   61.58   69.18  121.81   70.16  155.12   69.69
  188.09   67.38  233.18   53.01  246.65   50.29  266.07    51.9  328.97   51.26
  353.82   56.58  366.41   56.85  369.93   54.79  391.93   53.23   396.4   47.06
  403.43   41.22  408.56   39.88  417.32   41.57  423.14   51.83  448.88   55.46
  473.95   62.66  499.57   65.55  511.38   68.53  668.27   70.89  745.05   66.03
  810.32   70.93  924.17   72.46  955.51   70.76 1002.96   54.41 1042.17   54.06
#Mann= 5 ,-1 , 0
       0     .99       0  155.12     .07       0  403.43    .035       0
  417.32     .07       0  511.38     .99       0
#Block Obstruct= 2 , 0
       0                  955.51       0   70.76
Bank Sta=155.12,511.38
XS Rating Curve= 0
Exp/Cntr=.3,.1

Type RM Length L Ch R = 1 ,1681.007,25.38,210.59,211.92
XS GIS Cut Line= 4
     3059352.479    13841758.898     3059216.563    13841444.323
      3059128.31     13841432.06      3058553.14    13841197.505
#Sta/Elev= 30
       0   70.37   28.97   69.31   49.71   70.32   87.65   68.07  127.08   68.07
  188.33   69.53   330.4   67.19  377.89   60.74  391.19   52.95  406.93   41.33
     412   41.06  416.09   39.46  422.19   39.28  428.07   40.43  440.19   49.55
  473.93   60.19  519.96   65.38  556.03   67.85  625.02   68.45  645.72   69.32
  714.07   68.73  786.01    69.4  842.66    71.5  893.58   66.32  916.39   65.71
  946.61   70.59 1003.25   71.07 1011.94   69.56 1049.63   69.79 1052.94    67.3
#Mann= 5 ,-1 , 0
       0     .99       0   330.4     .07       0     412    .035       0
  428.07     .07       0  556.03     .99       0
Bank Sta=330.4,556.03
XS Rating Curve= 0
Exp/Cntr=.3,.1

Type RM Length L Ch R = 1 ,1481.135,47.37,256.27,497.52
BEGIN DESCRIPTION:
Other ditch system to the Buffalo Bayou blocked
END DESCRIPTION:
XS GIS Cut Line= 5
     3059388.034     13841931.55     3059378.249    13841825.314
     3059212.381     13841249.85     3059164.286    13841214.301
     3058607.526    13841002.562
#Sta/Elev= 30
       0   70.45   44.95   71.12  155.91   69.58  170.75   70.28  219.54   67.44
  309.82   68.99  441.18   68.14  464.46   67.32  506.13   60.27  535.41   57.57
  540.36   56.34  583.74   57.38  642.15   54.37  651.15   51.85  661.15   41.75
  672.26   40.78  681.15   42.05  701.24   52.83   734.5   60.21  751.75   67.08
  777.47   69.86  831.89   69.48  874.56    67.4  912.91   69.93  987.92   69.74
 1024.22   68.21 1136.41   68.45 1224.94   59.77 1264.64   52.04 1361.05   50.79
#Mann= 5 ,-1 , 0
       0     .99       0  441.18     .07       0  661.15    .035       0
  681.15     .07       0  777.47     .99       0
#Block Obstruct= 2 , 0
       0                 1136.41       0   68.45
Bank Sta=441.18,777.47
XS Rating Curve= 0
Exp/Cntr=.3,.1

Type RM Length L Ch R = 1 ,1246.119,49.59,74.8,51.21
BEGIN DESCRIPTION:
A
END DESCRIPTION:
XS GIS Cut Line= 4
     3059403.092    13841939.355     3059342.292    13841398.255
      3059420.91    13841290.879     3059488.026    13840734.969
#Sta/Elev= 30
       0   69.57  112.43   71.09  293.56   69.64  336.79   65.89  407.96   67.32
  500.91   65.48  518.81   64.24  534.47   58.56  545.56   55.96  560.27   49.46
  564.58   48.52  573.68   48.45  579.02   40.81  581.84   39.89  590.41   39.81
  593.25    40.7  599.98   41.24  608.92   47.75  647.92   65.42  660.86   66.53
  665.79   67.76  838.59   68.17  885.84   69.75  915.24      72 1015.83   70.93
 1054.84   73.28 1114.85   70.72  1128.6   69.35 1206.47   66.84 1237.53   68.91
#Mann= 6 ,-1 , 0
       0     .99       0  407.96     .07       0  579.02    .035       0
  599.98     .07       0  660.86     .05       0  838.59     .99       0
Bank Sta=500.91,660.86
XS Rating Curve= 0
Exp/Cntr=.5,.3

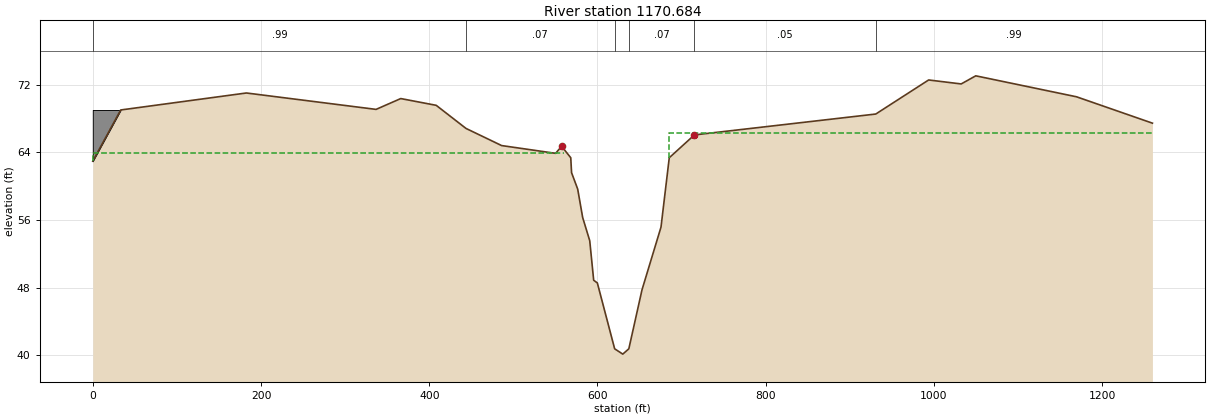
Type RM Length L Ch R = 1 ,1170.684,12.95,14.02,13.53
BEGIN DESCRIPTION:
u/s face of Wastewater Treatment Bridge
END DESCRIPTION:
XS GIS Cut Line= 5
     3059419.852    13842010.273      3059415.09    13841449.786
     3059473.197    13841311.274     3059483.915    13841289.697
     3059510.353    13840765.467
#Sta/Elev= 30
       0   62.94   33.21      69  182.65   71.01  336.76   69.07  366.12   70.35
  408.28   69.55  443.63   66.82  486.05   64.79  550.21   63.87  557.36  64.705
  568.22   63.35  569.19   61.58  576.44   59.65  582.41   56.27  590.79   53.53
  595.47   48.86  599.82   48.54   620.4   40.75  630.08   40.12  637.26   40.75
  652.92   47.73  675.49   55.14  685.32   63.35  715.22   66.05  930.81   68.52
  993.67   72.55 1032.35   72.08 1049.68   73.04 1169.47   70.56  1259.7   67.44
#Mann= 6 ,-1 , 0
       0     .99       0  443.63     .07       0   620.4    .035       0
  637.26     .07       0  715.22     .05       0  930.81     .99       0
#XS Ineff= 2 , 0
       0  560.51   63.94  685.32       0   66.25
Permanent Ineff=
       F       F
#Block Obstruct= 2 , 0
       0   33.21      69               0
Bank Sta=557.36,715.22
XS Rating Curve= 0
Exp/Cntr=.5,.3