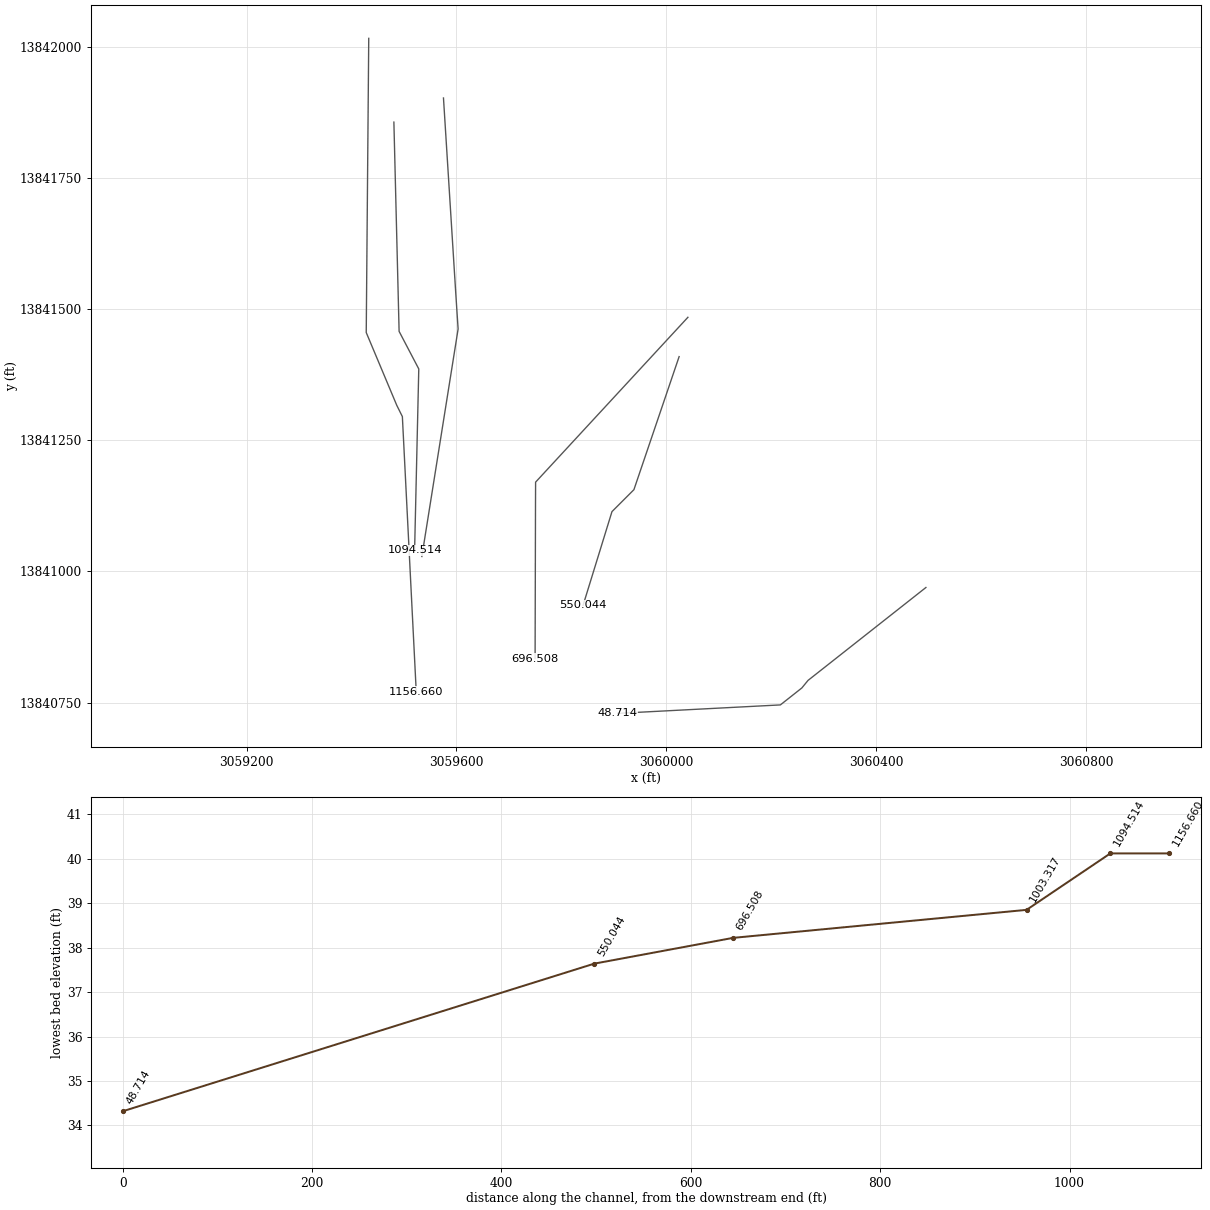
HEC-RAS study W156-00-00.prj: W156-00-00

--- W156-00-00.g02 (geometry) --- (continued)

Type RM Length L Ch R = 3 ,1163.716,,,
BEGIN DESCRIPTION:
Wastewater Treatment Bridge
END DESCRIPTION:
Bridge Culvert--1,0,-1,-1, 0
Deck Dist Width WeirC Skew NumUp NumDn MinLoCord MaxHiCord MaxSubmerge Is_Ogee
.01,14,2.6,0, 6, 6, 65.75, , .95, 0, 0,0,,
  560.98  565.86  565.86  688.68  688.68  718.22
   66.25   66.25   66.25   66.25   66.25   66.25
   63.35   63.35   63.35   63.35   63.35   63.35
  543.67  548.55  548.55  671.37  671.37  700.91
   66.25   66.25   66.25   66.25   66.25   66.25
   63.35   63.35   63.35   63.35   63.35   63.35
Pier Skew, UpSta & Num, DnSta & Num=  ,604.66, 4 ,587.35, 4 , 3 , 3 , 0 ,,
     1.5     1.5     2.6     2.6
   41.05   60.75   60.75   60.75
     1.5     1.5     2.6     2.6
   41.05   60.75   60.75   60.75
Pier Skew, UpSta & Num, DnSta & Num=  ,648.48, 4 ,631.17, 4 , 3 , 3 , 0 ,,
     1.5     1.5     2.6     2.6
   41.05   60.75   60.75   60.75
     1.5     1.5     2.6     2.6
   41.05   60.75   60.75   60.75
BR Coef=-1 , 1 , 1 ,1.25, 0 ,,,.8,-1,2,0,
WSPro=,,,, 1 ,,,, 0 ,,,, 0 ,,,,-1 ,-1 ,-1 , 0 , 0 , 0 , 0 , 0
BC Design=,, 0 ,, 0 ,,,,,,
BC HTab HWMax=73.04

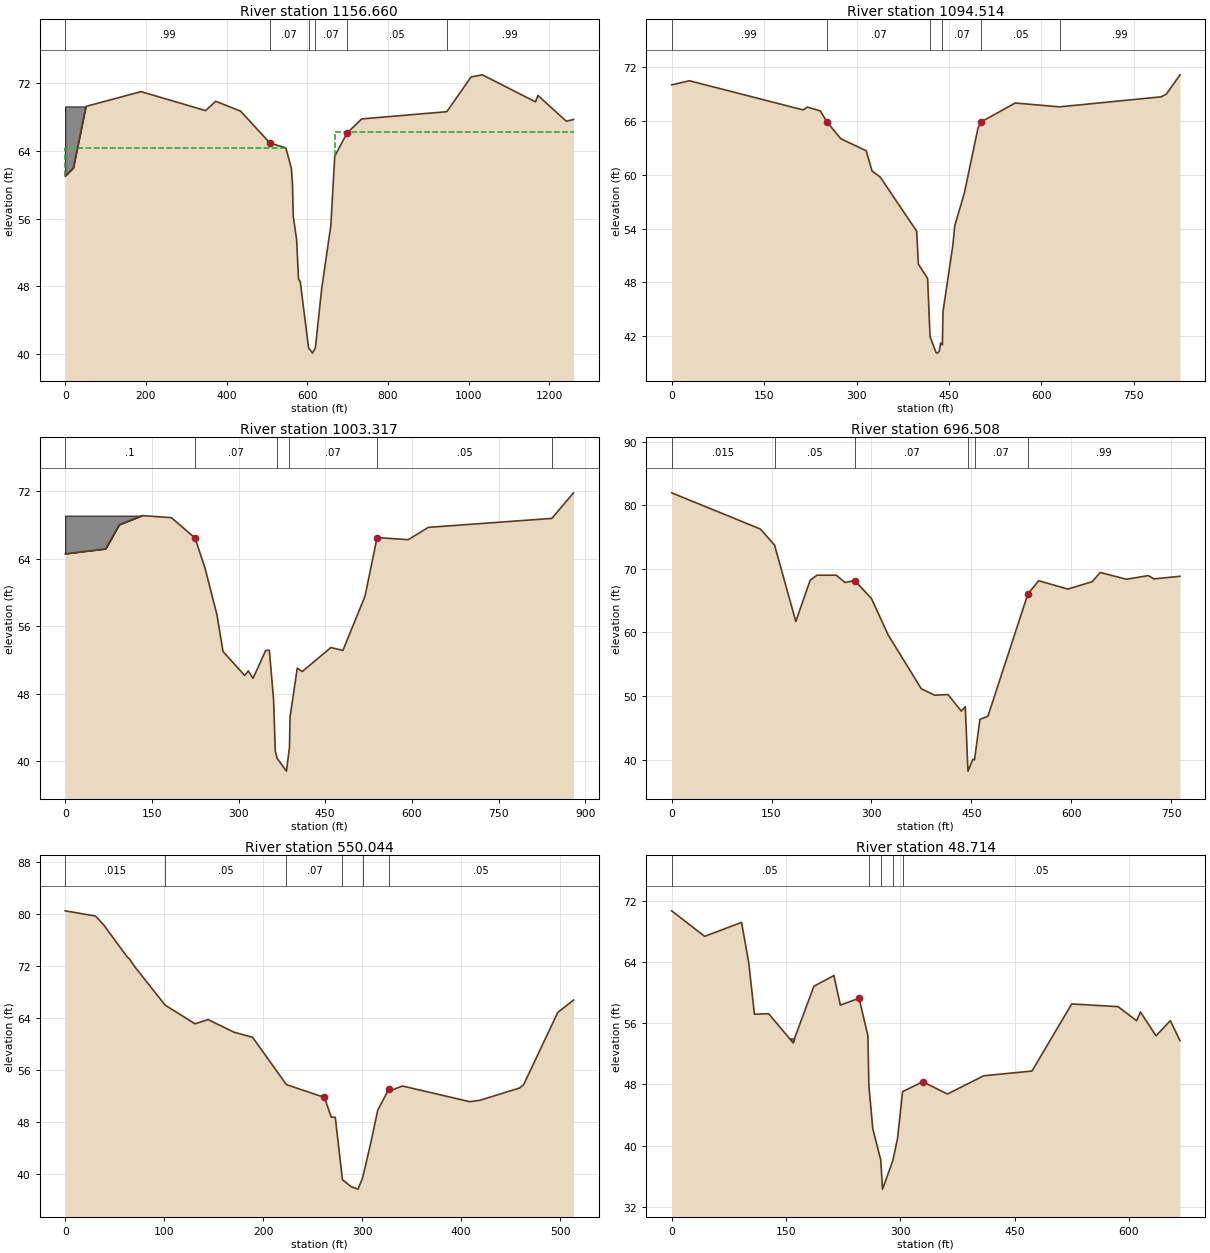
Type RM Length L Ch R = 1 ,1156.660,57.69,62.33,15.47
BEGIN DESCRIPTION:
d/s face of Wastewater Treatment Bridge
END DESCRIPTION:
XS GIS Cut Line= 5
     3059432.815    13842015.581     3059428.053    13841455.094
      3059486.16    13841316.582     3059496.878    13841295.005
     3059523.316    13840770.775
#Sta/Elev= 30
       0   61.02   20.22   61.98   51.32   69.22  187.96   70.97  347.79   68.73
  373.04   69.83  434.82   68.66  507.34    64.9  546.86   64.33  560.51    61.9
  563.18   60.17   565.1   56.27  573.48   53.53  578.16   48.86  582.51   48.54
  603.09   40.75  612.77   40.12  619.95   40.75  635.61   47.73  658.18   55.14
  668.01   63.35  697.91   66.05  734.81   67.75  945.63    68.6 1005.78    72.7
 1033.69   72.95 1165.44   69.76 1171.52   70.52 1241.78   67.48  1259.7   67.68
#Mann= 6 ,-1 , 0
       0     .99       0  507.34     .07       0  603.09    .035       0
  619.95     .07       0  697.91     .05       0  945.63     .99       0
#XS Ineff= 2 , 0
       0  546.86   64.33  668.01       0   66.25
Permanent Ineff=
       F       F
#Block Obstruct= 2 , 0
       0   51.32   69.22               0
Bank Sta=507.34,697.91
XS Rating Curve= 0
Exp/Cntr=.5,.3

Type RM Length L Ch R = 1 ,1094.514,107.69,88.47,24.05
XS GIS Cut Line= 4
     3059480.727    13841855.991     3059490.664    13841457.295
     3059528.138    13841385.772     3059520.196    13841040.414
#Sta/Elev= 30
       0   70.02   28.77   70.48  213.22   67.23  220.58   67.54  241.25   67.12
  251.64   65.93  274.52   64.01  315.67   62.68  325.18   60.43  338.62   59.73
  397.67   53.71  400.36   50.05  415.36   48.45  419.36   41.95   429.1   40.18
  431.22   40.12  434.43   40.35  436.44   41.24  439.36   41.05  440.36   44.75
  456.36   52.15  459.42   54.32  474.92   57.94  497.17    65.2  502.44    65.9
  557.62      68  629.44   67.57  794.58   68.69  802.84   68.99  825.01   71.14
#Mann= 6 ,-1 , 0
       0     .99       0  251.64     .07       0  419.36    .035       0
  439.36     .07       0  502.44     .05       0  629.44     .99       0
Bank Sta=251.64,502.44
XS Rating Curve= 0
Exp/Cntr=.3,.1

Type RM Length L Ch R = 1 ,1003.317,427.86,309.98,210.67
BEGIN DESCRIPTION:
Beltway 8 area blocked
END DESCRIPTION:
XS GIS Cut Line= 4
     3059575.189    13841901.926     3059598.918    13841524.954
     3059603.081    13841461.899     3059533.998    13841028.473
#Sta/Elev= 30
       0    64.6   70.01   65.18    93.5   68.04  133.21   69.12  183.75   68.88
  224.74   66.46     242    62.9  262.48   57.43  273.16   53.02   310.6   50.19
  316.87   50.73  325.11   49.85     347   53.14   353.3   53.18  360.65   47.35
  363.65   41.21  366.99   40.36  382.93   38.85  388.15   41.68  389.15   45.26
  401.65   51.05  410.29   50.65  459.85   53.49  480.67   53.15  518.78   59.55
  539.81   66.52  593.78   66.27  628.43   67.73  842.24   68.79  879.81   71.82
#Mann= 6 ,-1 , 0
       0      .1       0  224.74     .07       0  366.99    .035       0
  388.15     .07       0  539.81     .05       0  842.24     .99       0
#Block Obstruct= 2 , 0
       0  133.21   69.12               0
Bank Sta=224.74,539.81
XS Rating Curve= 0
Exp/Cntr=.3,.1

Type RM Length L Ch R = 1 ,696.508 ,93.43,146.68,125.36
XS GIS Cut Line= 4
     3060040.841    13841484.134     3059750.692    13841170.112
     3059750.511    13841129.628     3059749.738    13840834.126
#Sta/Elev= 30
       0   81.94  133.28   76.25  154.51   73.74  186.46   61.73  208.04   68.21
   218.2      69  247.12      69  260.39   67.86  275.03   68.15  300.03   65.35
  325.03   59.65  375.03   51.15  395.03   50.15  415.03   50.25  435.03   47.65
  441.03   48.35  445.03   38.22   452.5   40.09  454.86   39.98  463.03   46.35
  475.03   46.85  535.03   66.05  551.31   68.13  595.03   66.82  631.63   67.98
  643.72   69.43  683.15   68.36  715.88   68.94  724.36   68.42  763.53   68.83
#Mann= 6 ,-1 , 0
       0    .015       0  154.51     .05       0  275.03     .07       0
  445.03    .035       0  454.86     .07       0  535.03     .99       0
Bank Sta=275.03,535.03
XS Rating Curve= 0
Exp/Cntr=.3,.1

Type RM Length L Ch R = 1 ,550.044 ,565.31,498,340.16
XS GIS Cut Line= 4
     3060024.123     13841409.24     3059937.995     13841155.75
     3059896.173    13841113.928     3059841.163    13840935.519
#Sta/Elev= 30
       0   80.54   30.68   79.73   38.77   78.39   62.53   73.46   65.07   73.09
   70.44   71.89  100.94   66.01  131.22   63.12  144.28   63.78  170.55   61.83
  189.31   61.04  223.49   53.75  261.84   51.78  268.83   48.73  272.86   48.72
  280.08    39.1  288.91   38.02  295.84   37.64  300.45   39.37  308.28   44.47
  315.79   49.82  326.87   53.02  329.64   52.88  340.68   53.54  408.76   51.12
  419.07   51.34  459.03   53.23  463.21   53.76   497.6   64.87  513.56   66.79
#Mann= 6 ,-1 , 0
       0    .015       0  100.94     .05       0  223.49     .07       0
  280.08    .035       0  300.45     .07       0  326.87     .05       0
Bank Sta=261.84,326.87
XS Rating Curve= 0
Exp/Cntr=.3,.1

Type RM Length L Ch R = 1 ,48.714  ,38.9,7.41,84.79
XS GIS Cut Line= 5
     3060494.273    13840969.395     3060269.709    13840792.409
     3060257.919    13840778.024     3060216.993    13840745.712
      3059907.12    13840729.588
#Sta/Elev= 30
       0   70.66   43.24   67.33    91.7   69.15  101.13   63.87  108.57   57.16
  127.24   57.23  159.16   53.45  186.58   60.81  212.87   62.21  221.33   58.35
  245.92   59.25  257.51   54.33  258.73   47.82  263.92   42.19  274.31   38.14
  276.67   34.32  290.02   37.99  296.37   40.93  302.95   47.05  329.36   48.34
  361.85   46.74  409.39   49.12  472.77   49.74  524.88    58.5  585.56   58.15
  610.03   56.31     615   57.46   635.5   54.34  654.26   56.32  666.96   53.71
#Mann= 5 ,-1 , 0
       0     .05       0  258.73     .07       0  274.31    .035       0
  290.02     .07       0  302.95     .05       0
#Block Obstruct= 2 , 0
       0  160.88      54  654.26       0      56
Bank Sta=245.92,329.36
XS Rating Curve= 0
Exp/Cntr=.3,.1

Chan Stop Cuts=-1